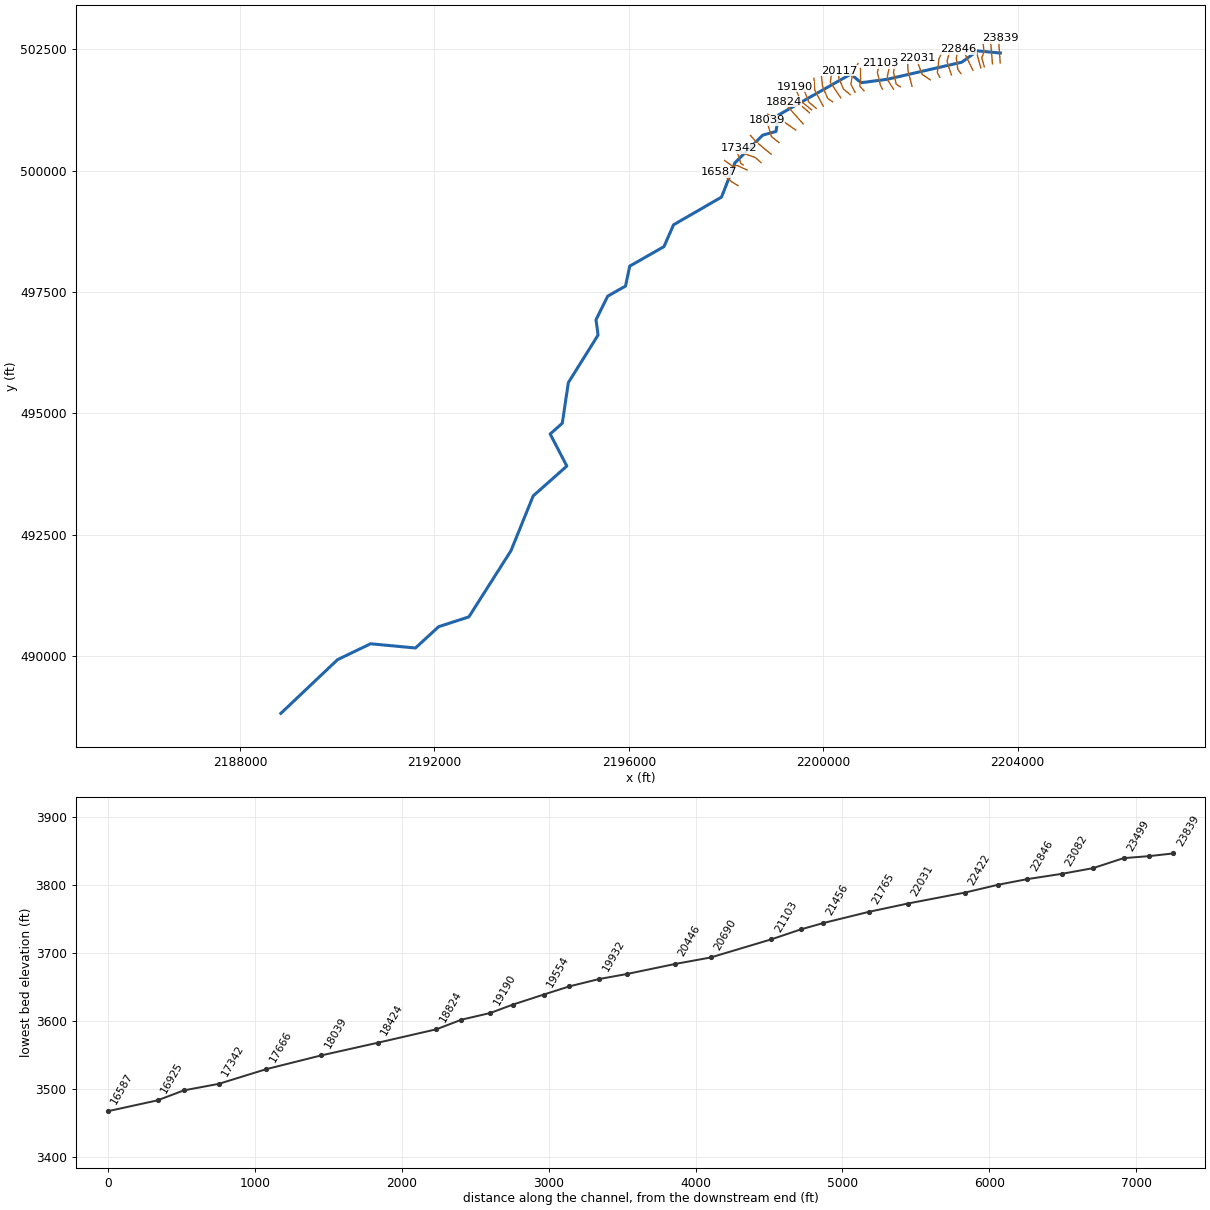
--- TEACK.prj (project) ---

Proj Title=TEACK
Current Plan=p01
Default Exp/Contr=0,0
English Units
Geom File=g01
Flow File=f01
Plan File=p01
Background Map Layer=Inundation Boundary (01pct Value_0)
Background Map Layer=Inundation Boundary (01pct Value_0)
Background Map Layer=QC
BEGIN DESCRIPTION:
----------MODEL BY WOOD PLC 2021----------
Stream Name: Tea Creek
Flood Zone: Enhanced Approximate
Pocahontas County, WV
HEC-RAS Version: RAS 6.1
Vertical Datum: NAVD88
Projection: NAD 1983 StatePlane West Virginia S FIPS 4702 (US Feet)
Terrain: 1-meter LIDAR (FEMA Region III 3DEP collected 2016-2018)
Land Use: 2019 NLCD
Hydrologic Method:
WV SIR2010-5033 regression equations
END DESCRIPTION:
DSS Export Rating Curves= 0
DSS Export Rating Curve Sorted= 0
DSS Export Volume Flow Curves= 0
DXF OffsetX= 0
DXF OffsetY= 0
DXF ScaleX= 0
DXF ScaleY= 0

--- TEACK.p01 (plan) ---

Plan Title=Floodplain
Program Version=6.10
Short Identifier=Floodplain
Geom File=g01
Flow File=f01
Subcritical Flow
K Sum by GR= 0
Std Step Tol= 0.01
Critical Tol= 0.01
Num of Std Step Trials= 20
Max Error Tol= 0.3
Flow Tol Ratio= 0.001
Split Flow NTrial= 30
Split Flow Tol= 0.02
Split Flow Ratio= 0.02
Log Output Level= 0
Friction Slope Method= 1
Unsteady Friction Slope Method= 2
Unsteady Bridges Friction Slope Method= 1
Parabolic Critical Depth
Global Vel Dist= 0 , 0 , 0
Global Log Level= 0
CheckData=True
Encroach Param=-1 ,0,0, 0
Mapping Interval=1HOUR
Computation Time Step Use Courant=        0
Computation Time Step Use Time Series=    0
Computation Time Step Count To Double=0
Computation Time Step Max Doubling=0
Computation Time Step Max Halving=0
Computation Time Step Residence Courant=0
Run HTab= 0
Run UNet= 0
Run Sediment= 0
Run PostProcess= 0
Run WQNet= 0
Run RASMapper=-1
UNET Theta= 0
UNET Theta Warmup= 0
UNET ZTol= 0
UNET ZSATol= 0
UNET MxIter= 0
UNET Max Iter WO Improvement= 0
UNET MaxInSteps= 0
UNET DtIC= 0
UNET DtMin= 0
UNET MaxCRTS= 0
UNET WFStab= 0
UNET SFStab= 0
UNET WFX= 1
UNET SFX= 1
UNET Gravity=32.174
UNET 1D Methodology=Finite Difference
UNET DSS MLevel= 1
UNET Pardiso=0
UNET DZMax Abort= 0
UNET Use Existing IB Tables= 0
UNET Froude Reduction=False
UNET Froude Limit= 0
UNET Froude Power= 0
UNET D1 Cores= 0
UNET WindReference=Eulerian
UNET WindDragFormulation=Hsu (1988)
UNET D2 Coriolis=0
UNET D2 Cores= 0
UNET D2 Theta= 1
UNET D2 Theta Warmup= 1
UNET D2 Z Tol= 0.01
UNET D2 Volume Tol= 0.01
UNET D2 Max Iterations= 20
UNET D2 Equation= 0
UNET D2 RampUpFraction=0.1
UNET D2 TimeSlices= 1
UNET D2 Turbulence Formulation=Non-Conservative (original)
UNET D2 Eddy Viscosity=0.3
UNET D2 Transverse Eddy Viscosity=0.1
UNET D2 Smagorinsky Mixing=0
UNET D2 BCVolumeCheck=0
UNET D2 Cores=0
UNET D2 SolverType=PARDISO (Direct)
UNET D2 Minimum Iterations= 2147483647
UNET D2 Maximum Iterations= 2147483647
UNET D2 Restart Number= 10
UNET D2 Relaxation Coeff=1.3
UNET D2 SOR Precondition Iterations= 10
UNET D2 ILUT Maximum Fill= 8
UNET D2 ILUT Tolerance=1E-08
UNET D1D2 MaxIter= 0
UNET D1D2 ZTol=0.01
UNET D1D2 QTol=0.1
UNET D1D2 MinQTol=1
Write IC File= 0
Write IC File at Fixed DateTime=0
Write IC File at Sim End=0
Echo Input=False
Echo Parameters=False
Echo Output=False
Write Detailed= 0
HDF Write Warmup=0
HDF Write Time Slices=0
HDF Flush=0
HDF Compression= 1
HDF Chunk Size= 1
HDF Spatial Parts= 1
HDF Use Max Rows=0
HDF Fixed Rows= 1
Calibration Method= 0
Calibration Iterations= 20
Calibration Max Change=0.05
Calibration Tolerance=0.2
Calibration Maximum=1.5
Calibration Minimum=0.5
Calibration Optimization Method= 1
WQ AD Non Conservative
WQ ULTIMATE=-1
WQ Max Comp Step=1HOUR
WQ Output Interval=15MIN
WQ Output Selected Increments= 0
WQ Output face flow=0
WQ Output face velocity=0
WQ Output face area=0
WQ Output face dispersion=0
WQ Output cell volume=0
WQ Output cell surface area=0
WQ Output cell continuity=0
WQ Output cumulative cell continuity=0
WQ Output face conc=0
WQ Output face dconc_dx=0
WQ Output face courant=0
WQ Output face peclet=0
WQ Output face adv mass=0
WQ Output face disp mass=0
WQ Output cell mass=0
WQ Output cell source sink temp=0
WQ Output nsm pathways=0
WQ Output nsm derived pathways=0
WQ Create Restart=0
WQ Fixed Restart=0
WQ System Summary=0
WQ Write To DSS=0
Sorting and Armoring Iterations= 10
XS Update Threshold= 0.02
Bed Roughness Predictor= 0
Hydraulics Update Threshold= 0.02
Energy Slope Method= 1
Volume Change Method= 1
Sediment Retention Method= 0
Sediment TS Multiplier= 1
Warm Up Method= 0
XS Weighting Method= 0
Number of US Weighted Cross Sections= 1
Number of DS Weighted Cross Sections= 1
Upstream XS Weight=0
Main XS Weight=1
Downstream XS Weight=0
Number of DS XS's Weighted with US Boundary= 1
Upstream Boundary Weight= 1
Weight of XSs Associated with US Boundary= 0
Number of US XS's Weighted with DS Boundary= 1
Downstream Boundary Weight= 0.5
Weight of XSs Associated with DS Boundary= 0.5
Percentile Method= 0
Sediment Output Level= 3
Mass or Volume Output= 0
Output Increment Type= 1
Profile and TS Output Increment= 1
Transport Output Increment 1
XS Output Flag= 0
XS Output Increment= 10
Read HDF5 Sediment Hotstart= 0
Sediment Hotstart Type= 0
Write Gradation File= 0
Read Gradation Hotstart= 0
Write HDF5 File= 1
Write Binary Output= 1
Write DSS Sediment File= 0
DSS Sediment Output Type= 1
SV Curve= 0
Specific Gage Flag= 0
Subcell Erosion Methods= 0
Subcell Deposition Methods= 0
Advection Scheme= 1
Matrix Solver= 0
Implicit Weighting Factor= 1
Maximum Outer Loop Convergence Iterations= 5
Convergence Maximum Absolute= 0.001
Convergence RMSE= 0.0001
Grain Fractions Max Abs Error= 0.001
Max Subgrid Regions= 1
Max Subgrid Length Scale= 3.402823E+38
Initial Layer Thickness= 3.402823E+38
Min Layer Thickness= 3.402823E+38
Max Layer Thickness= 3.402823E+38
Number of Layers= 5

--- TEACK.f01 (steady flow) ---

Flow Title=Flow
Program Version=6.10
Number of Profiles= 6
Profile Names=01pct,10pct,04pct,02pct,0_2pct,01plus
River Rch & RM=TEACK,Main,23839
     572     302     402     484     799     846
River Rch & RM=TEACK,Main,23292
     636     338     448     539     887     941
River Rch & RM=TEACK,Main,20446
     708     377     500     600     985    1050
River Rch & RM=TEACK,Main,19343
     794     425     562     674    1100    1170
River Rch & RM=TEACK,Main,15668
    1630     896    1170    1390    2230    2410
River Rch & RM=TEACK,Main,7760
    1860    1030    1330    1590    2540    2740
River Rch & RM=TEACK,Main,6403
    2100    1160    1510    1790    2860    3100
Boundary for River Rch & Prof#=TEACK,Main            , 1
Up Type= 0
Dn Type= 3
Dn Slope=0.02073
Boundary for River Rch & Prof#=TEACK,Main            , 2
Up Type= 0
Dn Type= 3
Dn Slope=0.02073
Boundary for River Rch & Prof#=TEACK,Main            , 3
Up Type= 0
Dn Type= 3
Dn Slope=0.02073
Boundary for River Rch & Prof#=TEACK,Main            , 4
Up Type= 0
Dn Type= 3
Dn Slope=0.02073
Boundary for River Rch & Prof#=TEACK,Main            , 5
Up Type= 0
Dn Type= 3
Dn Slope=0.02073
Boundary for River Rch & Prof#=TEACK,Main            , 6
Up Type= 0
Dn Type= 3
Dn Slope=0.02073
DSS Import GetInterval= 0
DSS Import GetPeak= 0
DSS Import FillOption= 0

--- TEACK.g01 (geometry) ---

Geom Title=Geometry
Program Version=6.10

River Reach=TEACK           ,Main
Reach XY= 30
2203646.81013681502420.4830819822203173.59750055 502465.11192973
2202852.95509721502231.4778825642201319.07485788501880.183971372
2200779.81685506501808.6900142282200569.36911322501987.309079558
2199080.50791772501144.1421307332199028.92993689500805.151995063
2198756.10797597500729.9320011442198183.29908222500159.171987817
2197907.04405731499453.0529932232196920.67693555498883.615155727
2196722.21309364 498432.794863152196018.09606355498031.881951064
2195931.19203788497620.715122476 2195564.8479543497413.461928055
2195323.97409222496926.3070624772195366.53306222496612.522913143
2194754.78887889 495633.59409672 2194630.3911618494796.668933317
2194380.94927046494574.1688246052194723.30781437493913.945604999
2194031.68304163 493300.38189964 2193574.1019358492171.161060974
 2192707.1371343490807.6158878062192086.06226097490606.716027141
2191607.54451722490167.4239267262190685.11296314490254.384054646
2190005.58184189489927.9568859792188837.16488738488820.914480641

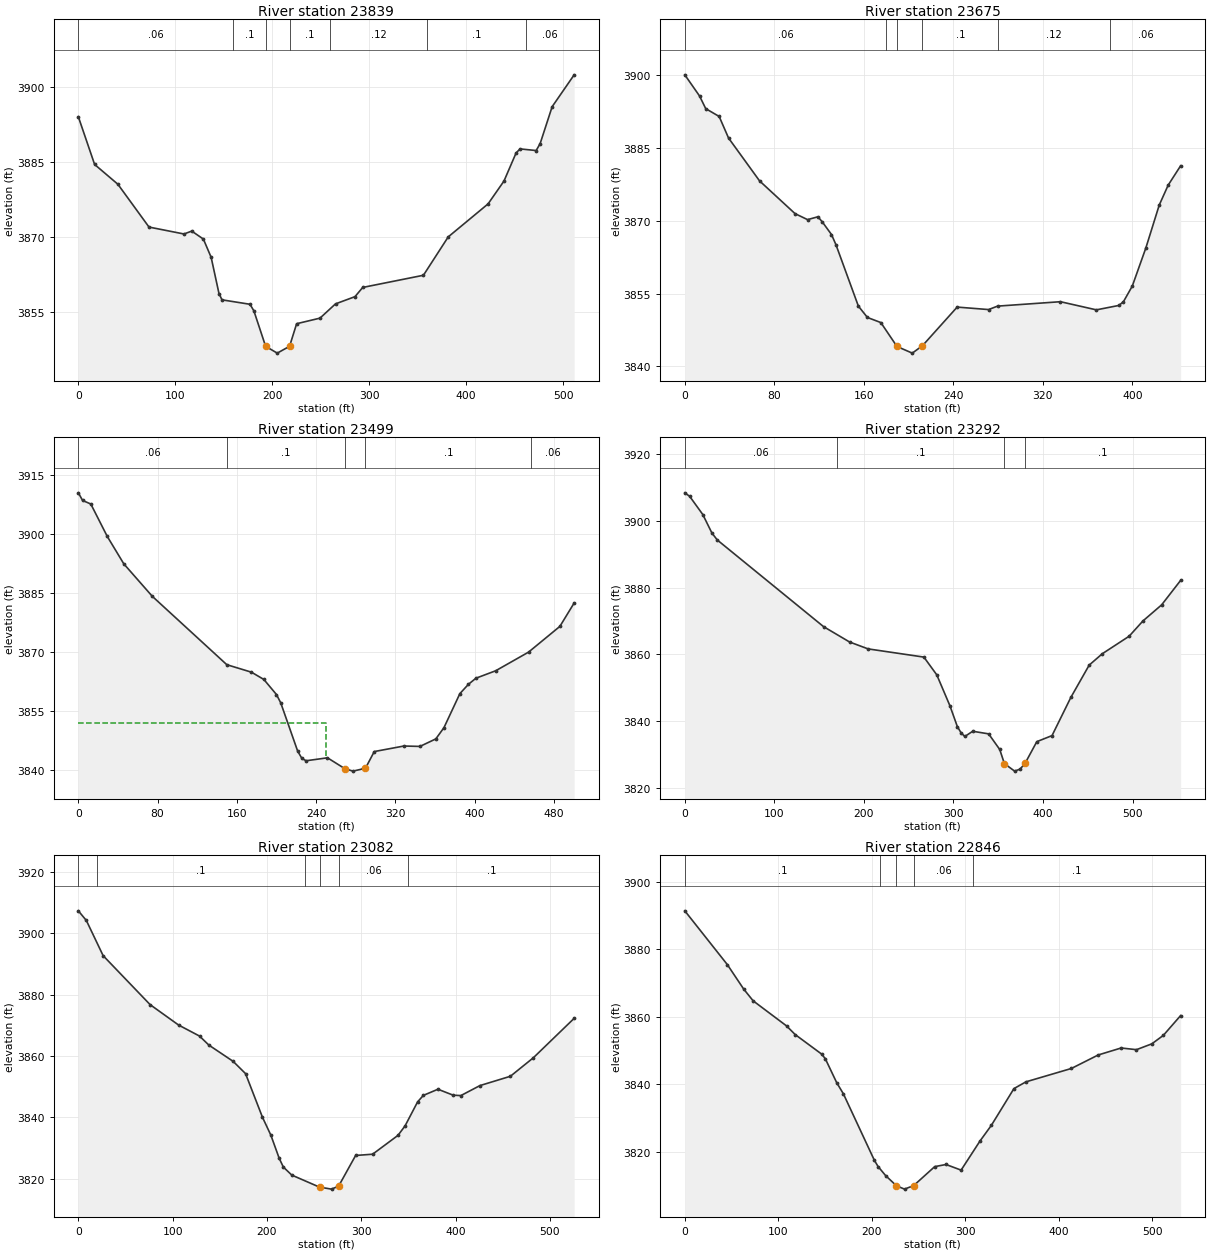
Type RM Length L Ch R = 1 ,23839   ,163.2,163.6,163.7
XS GIS Cut Line= 3
2203643.23707769502216.468349194 2203616.1277476502607.765067722
2203646.48332038 502723.09926233
#Sta/Elev= 30
       0 3894.13    16.8 3884.56    40.8 3880.59    72.9    3872     109 3870.61
     117 3871.19     129 3869.59     137 3865.94   145.1 3858.67   148.2  3857.4
   177.1 3856.51   181.1 3855.19   193.2 3848.08   205.2 3846.71   217.9 3848.08
   225.2 3852.61   249.3 3853.73   265.3 3856.59   285.4 3858.04   293.4 3859.89
     356 3862.33   381.6 3870.03   422.7 3876.65   439.1 3881.23   451.6 3886.87
   455.7 3887.68   472.3 3887.35   476.4 3888.74   488.8 3896.15   511.5 3902.54
#Mann= 7 ,-1,0
       0     .06       0     160      .1       0   193.2    .045       0
   217.9      .1       0     260     .12       0     360      .1       0
  462.23     .06       0
Bank Sta=193.2,217.9
XS Rating Curve= 0 ,0
Exp/Cntr=0.3,0.1

Type RM Length L Ch R = 1 ,23675   ,182,176.2,167.9
XS GIS Cut Line= 2
2203483.73129005502198.5527810572203447.94430893502640.216499238
#Sta/Elev= 30
       0 3900.12    13.2 3895.75    18.7 3893.15    30.7 3891.54    39.1 3887.09
    66.8 3878.26    98.5 3871.51   109.7 3870.27     119 3870.86     123 3869.76
   131.1  3867.2   135.1 3865.09   155.1 3852.45   163.2  3850.1   175.2 3849.05
   189.63844.124   203.3 3842.75   212.43844.278   243.4 3852.24   271.5 3851.73
   279.5 3852.44   335.7 3853.35   367.8 3851.67   387.9 3852.58     392 3853.35
   399.9 3856.57     412 3864.41     424 3873.28     432 3877.39   443.1 3881.37
#Mann= 6 ,-1,0
       0     .06       0     180      .1       0   189.6    .045       0
   212.4      .1       0     280     .12       0     380     .06       0
Bank Sta=189.6,212.4
XS Rating Curve= 0 ,0
Exp/Cntr(USF)=0,0
Exp/Cntr=0.3,0.1

Type RM Length L Ch R = 1 ,23499   ,182.4,207.3,235.3
XS GIS Cut Line= 4
2203316.10252261502137.0190359312203263.83180714502322.274791035
2203312.52394096502447.8577871752203289.36313412502619.401882364
#Sta/Elev= 30
       0 3910.54     4.3  3908.6    12.6 3907.69    29.2 3899.44    45.9 3892.46
    74.6 3884.21   149.8  3866.8   174.7 3864.89   187.2 3863.04   199.9 3859.21
   204.2 3857.11   221.3 3844.81   225.6 3842.93   229.9 3842.35   251.4  3843.1
268.91853840.336   277.1 3839.71289.69643840.434   298.6 3844.69   328.5  3846.1
   344.7    3846   360.7 3847.91   368.9 3850.76     385 3859.44   393.6  3861.8
   401.2 3863.36   421.1 3865.25   454.3    3870   485.9 3876.55   500.3 3882.51
#Mann= 5 ,-1,0
       0     .06       0     150      .1       0268.9185    .045       0
289.6964      .1       0  457.18     .06       0
#XS Ineff= 2 , 0
          250.17 3851.85
Permanent Ineff=
       F       F
Bank Sta=268.9185,289.6964
XS Rating Curve= 0 ,0
Exp/Cntr(USF)=0,0
Exp/Cntr=0.3,0.1

Type RM Length L Ch R = 1 ,23292   ,223.2,210.4,195.3
XS GIS Cut Line= 4
2203243.72883544502115.9622195692203157.41963646502425.621213887
2203071.74458059502448.1887956812203048.64539443502589.925705494
#Sta/Elev= 30
       0  3908.5     5.4 3907.46    20.1 3901.99    30.3 3896.43    36.3 3894.35
   154.9 3868.37     184 3863.75   204.7 3861.68     267 3859.22   281.4 3853.89
   296.1  3844.6   304.4 3838.34   308.5 3836.53   312.7  3835.4   321.5 3836.97
   339.3 3836.19   351.7  3831.5  356.893827.271   368.3 3825.01   374.4 3825.61
     380 3827.35   393.1 3833.85   410.1 3835.67   431.1 3847.12   451.6 3856.82
   466.3 3860.24   496.2 3865.48   511.6 3870.06   532.5 3874.89   553.7 3882.23
#Mann= 4 ,-1,0
       0     .06       0     170      .1       0  356.89    .045       0
     380      .1       0
Bank Sta=356.89,380
XS Rating Curve= 0 ,0
Exp/Cntr=0.3,0.1

Type RM Length L Ch R = 1 ,23082   ,240.5,236,231.3
XS GIS Cut Line= 3
2203081.41337436502065.5489282832202917.60201535502403.099607464
2202939.11259784 502552.01902475
#Sta/Elev= 30
       0 3907.24     8.5  3904.1    26.3 3892.65    76.1 3876.72   106.3 3870.08
   128.5 3866.49   138.3 3863.58   164.1 3858.27   177.3 3854.27   195.2 3840.09
   204.1 3834.27     213 3826.69   217.4 3823.86   226.3 3821.26   255.7 3817.34
   268.5 3816.69     276 3817.68     294 3827.64     312 3828.05   338.9 3834.18
   346.4 3837.26   359.7 3845.07   365.8 3847.19   381.3 3849.19   397.5 3847.25
   405.6 3847.13   425.8 3850.38   458.1 3853.41   482.4 3859.42   525.7 3872.26
#Mann= 6 ,-1,0
       0     .06       0      20      .1       0     240     .06       0
   255.7    .045       0     276     .06       0     350      .1       0
Bank Sta=255.7,276
XS Rating Curve= 0 ,0
Exp/Cntr(USF)=0,0
Exp/Cntr=0.3,0.1

Type RM Length L Ch R = 1 ,22846   ,197.6,198.4,200.6
XS GIS Cut Line= 4
 2202835.6839223501996.5740870812202771.14262746502083.798405781
2202740.46073789 502323.213893062202778.84057268502499.249039065
#Sta/Elev= 30
       0 3891.47    45.5  3875.5      63 3868.23    73.1 3864.75   108.8 3857.31
     118 3854.75   146.2 3848.97   150.2 3847.59   162.4 3840.47   169.6 3837.13
   202.7 3817.41   206.7 3815.56   214.7 3812.89   226.3 3809.86   234.9 3808.87
   244.7 3809.92   267.2 3815.55   279.3 3816.18   295.4 3814.51   315.6 3823.15
   327.7 3827.78   351.9 3838.71   364.7 3840.71   413.3 3844.68     442 3848.69
   466.5 3850.76   482.9 3850.26   499.3 3851.99   511.6  3854.5   530.1 3860.38
#Mann= 5 ,-1,0
       0      .1       0  208.51     .06       0   226.3    .045       0
   244.7     .06       0  308.51      .1       0
Bank Sta=226.3,244.7
XS Rating Curve= 0 ,0
Exp/Cntr=0.3,0.1

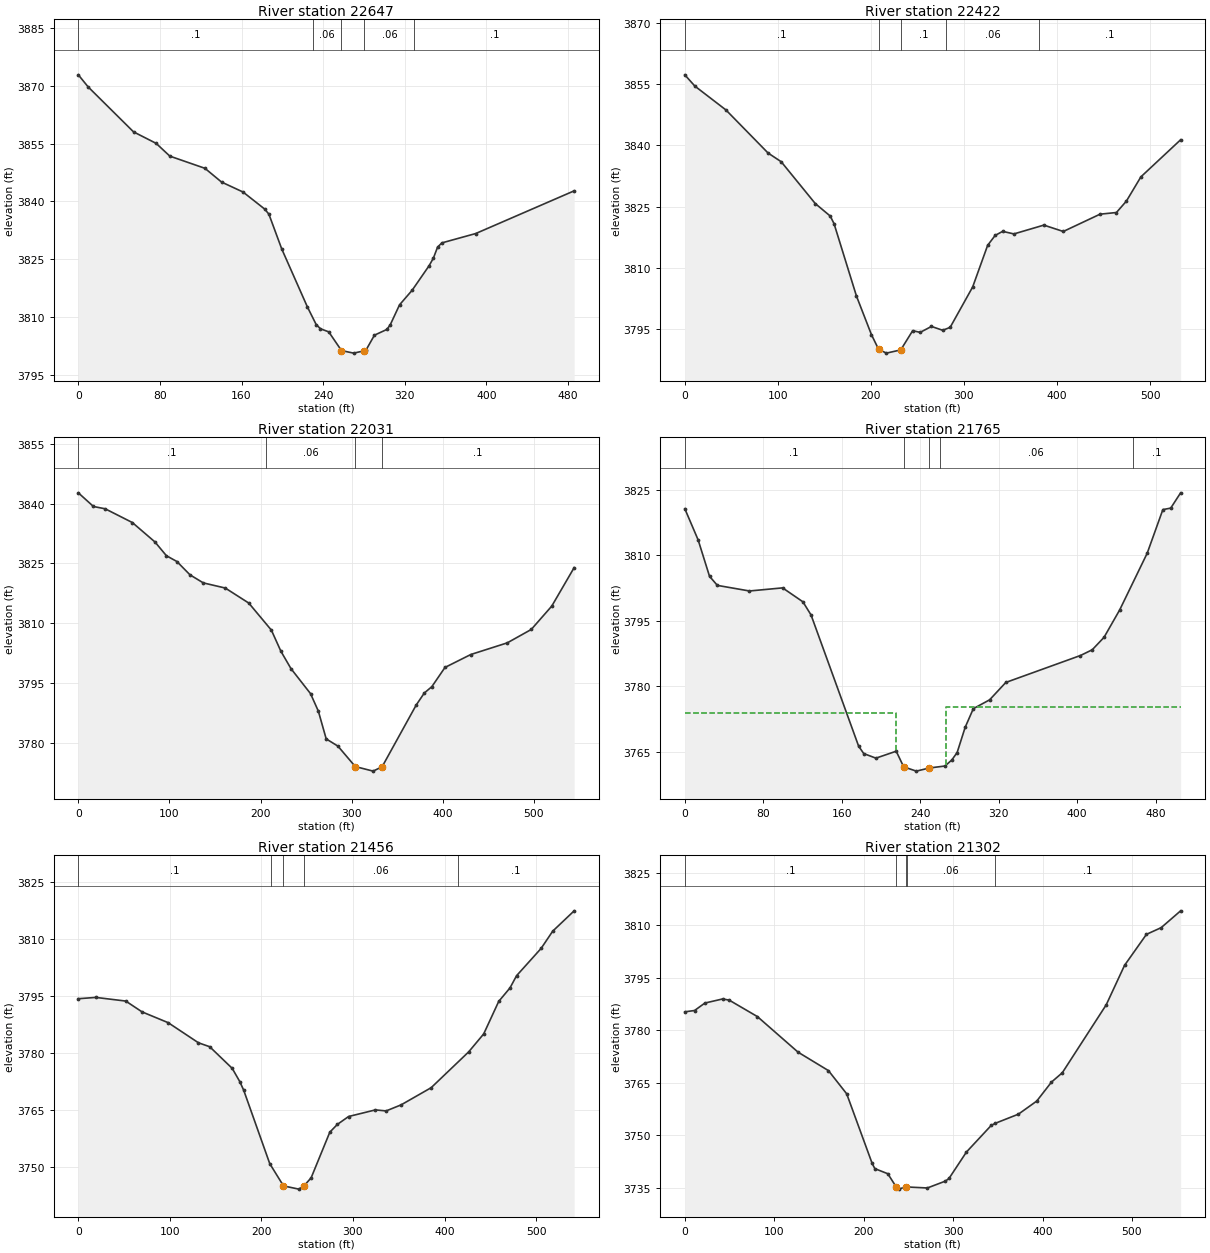
Type RM Length L Ch R = 1 ,22647   ,232.1,225.5,221.1
XS GIS Cut Line= 4
2202639.68224759501968.1195367882202564.61687256502191.569955473
 2202550.6512214502264.0167709062202597.78529409502434.223144513
#Sta/Elev= 30
       0 3872.84     9.6 3869.71    54.1 3858.04    76.3 3855.05    89.7 3851.74
   124.1 3848.58   140.4 3845.01   161.5 3842.42   182.6 3838.02   186.8 3836.69
   199.4 3827.66   224.5 3812.64   233.2 3808.02   237.4 3806.93   245.5 3806.13
     258 3801.27   269.9 3800.61   280.3 3801.21   282.2 3801.48   290.3 3805.27
   302.5 3806.76   305.8 3807.96   314.9 3813.14   327.3 3816.94   343.9  3823.3
   348.1 3825.27   352.2 3828.12   356.4 3829.22   389.6 3831.65   486.1 3842.73
#Mann= 5 ,-1,0
       0      .1       0     230     .06       0     258    .045       0
   280.3     .06       0   329.5      .1       0
Bank Sta=258,280.3
XS Rating Curve= 0 ,0
Exp/Cntr(USF)=0,0
Exp/Cntr=0.3,0.1

Type RM Length L Ch R = 1 ,22422   ,380.8,390.8,398
XS GIS Cut Line= 4
2202401.26844653501918.1503686172202349.20427848502015.957337906
2202382.80631056502301.3293784382202438.55998036502424.037679833
#Sta/Elev= 30
       0 3857.28    10.8 3854.52    44.2 3848.67    89.5 3838.11   103.6 3835.98
   140.2 3825.73   156.3 3822.66   160.4  3820.8   184.5 3803.05   200.6 3793.59
   208.3 3789.99   216.7 3789.06   232.1 3789.85   244.9 3794.56     253 3794.15
   265.1  3795.6   277.2 3794.66   285.2 3795.38   309.4 3805.28   325.5 3815.49
   333.6 3817.92   341.6 3818.91   353.7 3818.28   385.9 3820.44   406.8 3818.88
   446.3 3823.12   463.9 3823.53   474.6 3826.32   490.2 3832.27   532.9 3841.36
#Mann= 5 ,-1,0
       0      .1       0   208.3    .045       0   232.1      .1       0
   280.8     .06       0   380.8      .1       0
Bank Sta=208.3,232.1
XS Rating Curve= 0 ,0
Exp/Cntr=0.3,0.1

Type RM Length L Ch R = 1 ,22031   ,266.6,265.6,262.4
XS GIS Cut Line= 4
2202201.93952139501868.6925808132202039.78282257501977.900153489
2201955.39515277502193.0059784572201947.12185181502310.486852094
#Sta/Elev= 30
       0 3842.69    16.6 3839.26    29.5 3838.68    59.3 3835.23    84.1 3830.36
    96.7  3826.9   108.2 3825.45   122.6  3822.1   137.2 3820.08   161.3 3818.79
   187.1 3815.02   211.9 3808.23   222.4 3802.91   233.4 3798.57   254.9 3792.28
   263.5 3787.88   272.1 3780.92     285  3779.1     304 3773.98   323.6 3772.83
   333.5 3773.93   370.9 3789.42   379.8 3792.44   388.1 3794.04   402.5 3798.86
   430.8  3802.1   470.9 3805.03   497.2 3808.39   519.7 3814.25   544.3 3823.92
#Mann= 4 ,-1,0
       0      .1       0   205.5     .06       0     304    .045       0
   333.5      .1       0
Bank Sta=304,333.5
XS Rating Curve= 0 ,0
Exp/Cntr(USF)=0,0
Exp/Cntr=0.3,0.1

Type RM Length L Ch R = 1 ,21765   ,309.4,309.5,307.7
XS GIS Cut Line= 3
2201828.32653426501736.7681357492201745.12700982502052.476184417
2201737.72897076502231.222456568
#Sta/Elev= 30
       0 3820.64    13.6 3813.49    25.2 3805.16    33.2 3803.08    65.9  3801.8
    99.7 3802.51   120.4 3799.32   128.7  3796.3   177.2 3766.27   182.4 3764.58
   194.8 3763.53   215.5 3765.12   223.1 3761.54     236 3760.56   249.3 3761.28
   265.2 3761.73   272.2 3763.12   277.6 3764.82   285.8  3770.6   294.1 3774.86
   310.7 3776.88   327.2 3780.86   403.3 3787.03   415.3 3788.34   427.3 3791.18
   443.3 3797.47   471.3 3810.43   487.3 3820.43   495.3 3820.77   505.4 3824.27
#Mann= 5 ,-1,0
       0      .1       0   223.1    .045       0   249.3      .1       0
     260     .06       0  456.49      .1       0
#XS Ineff= 2 , 0
          215.67 3773.77  266.36         3775.31
Permanent Ineff=
       F       F
Bank Sta=223.1,249.3
XS Rating Curve= 0 ,0
Exp/Cntr=0.3,0.1

Type RM Length L Ch R = 1 ,21456   ,154.9,153.7,151.1
XS GIS Cut Line= 4
2201586.89709679501725.3395336332201501.90228138501779.464301134
2201446.11525914 502027.137529552201486.88811635502209.608000196
#Sta/Elev= 30
       0 3794.25    19.2 3794.59    51.8 3793.63    69.6 3790.78    98.1 3787.94
   131.2 3782.64   143.5  3781.6   168.1  3775.9   176.3 3772.44   180.6 3770.17
   209.1  3750.8   224.1 3744.94   240.8 3744.09     246 3744.82   254.3 3747.07
   274.7 3759.09   282.9 3761.13   295.2 3763.22   324.5 3764.96   336.2 3764.69
   352.6 3766.29   385.4 3770.81   426.4 3780.25   442.8 3784.98   459.2 3793.54
   471.5 3797.09   478.7 3800.31   505.5  3807.5   518.2 3812.05   541.6  3817.4
#Mann= 5 ,-1,0
       0      .1       0  210.77     .06       0   224.1    .045       0
     246     .06       0  414.64      .1       0
Bank Sta=224.1,246
XS Rating Curve= 0 ,0
Exp/Cntr=0.3,0.1

Type RM Length L Ch R = 1 ,21302   ,195.4,199.3,200.3
XS GIS Cut Line= 4
2201446.94920686501676.8802582272201328.84683831501860.866999127
2201320.47457689501938.9855490452201374.08556711502190.552489531
#Sta/Elev= 30
       0 3785.26    10.9 3785.64    22.5 3787.77    42.2 3788.93    49.6 3788.61
    81.2  3783.9   126.7 3773.74   160.6 3768.49     181 3761.87   209.5 3741.99
   212.5 3740.51     227 3739.05   236.2 3735.36   239.1 3734.66   247.1 3735.29
   271.2 3734.99   291.4 3736.95   295.4  3737.7   314.9 3745.24   342.6 3752.84
   347.2 3753.45     373 3756.05   393.5 3759.79     410 3765.21   422.1 3767.87
   471.2 3787.26   491.7 3798.53   516.2 3807.38   532.6 3809.28   554.4 3814.09
#Mann= 5 ,-1,0
       0      .1       0   236.2    .045       0   247.1      .1       0
  248.63     .06       0   347.2      .1       0
Bank Sta=236.2,247.1
XS Rating Curve= 0 ,0
Exp/Cntr(USF)=0,0
Exp/Cntr=0.3,0.1

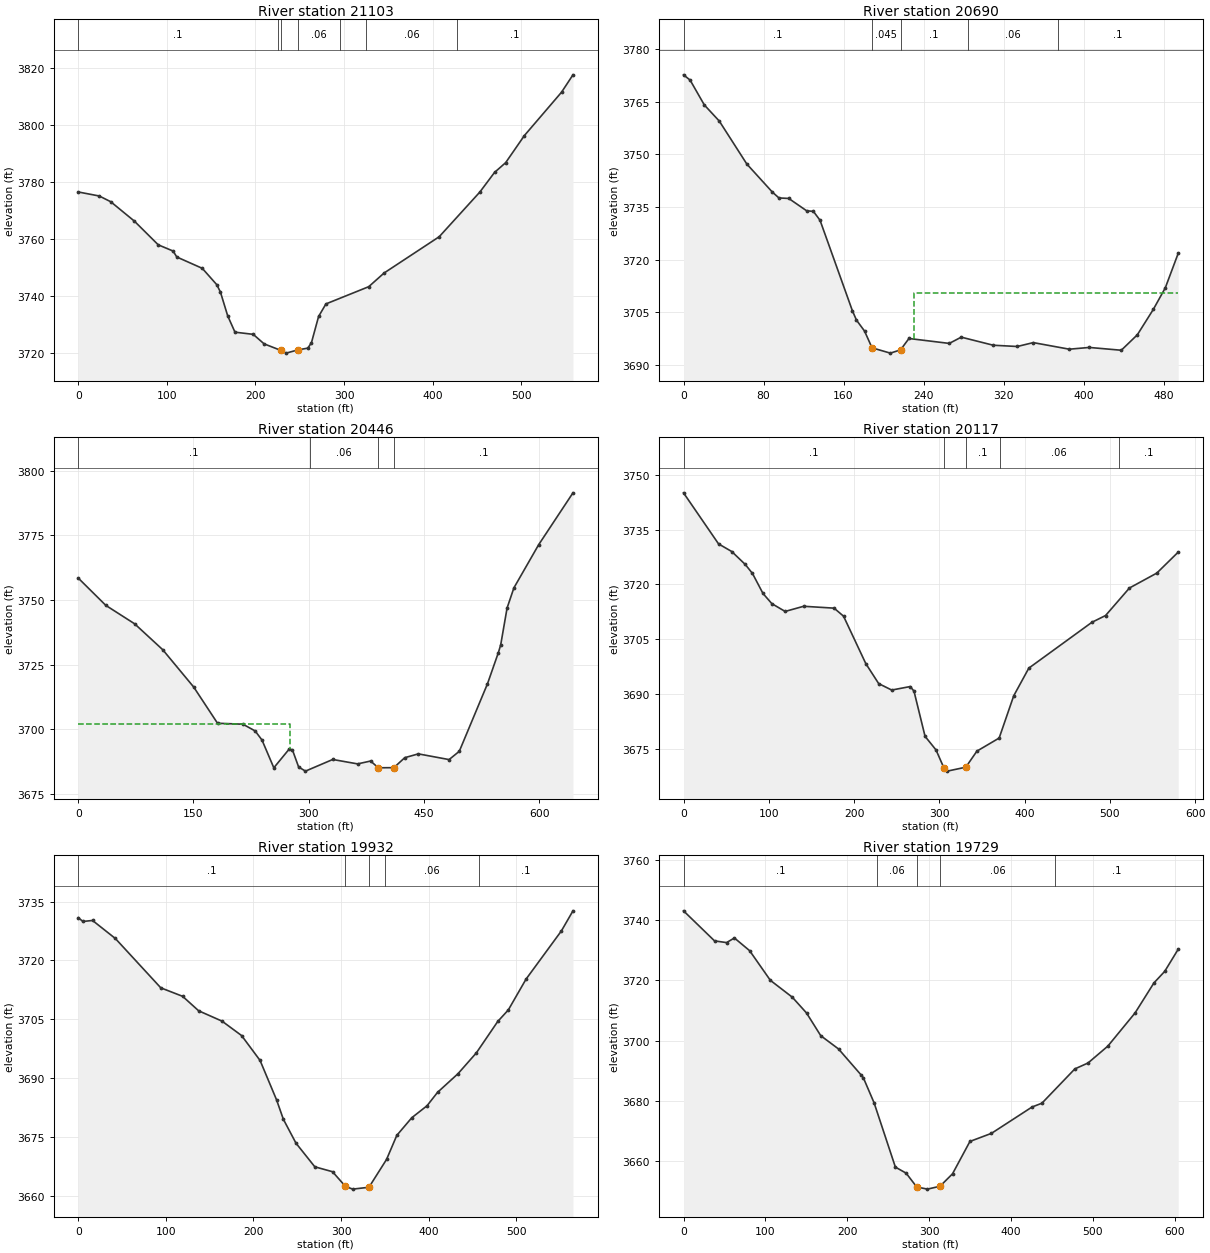
Type RM Length L Ch R = 1 ,21103   ,418,413.1,404.8
XS GIS Cut Line= 4
2201218.80673762501676.4662812322201176.21305849501761.533789047
2201114.29751427502026.4451357062201167.78323269502210.114136097
#Sta/Elev= 30
       0 3776.64    23.7 3775.23    36.6 3773.23    63.4  3766.4    90.3  3758.1
   107.1 3755.92   111.2 3753.84     140 3749.86   156.4 3744.11   160.5 3741.53
   168.7 3733.19   176.9 3727.47   197.5 3726.71   209.8 3723.37   228.6 3721.09
   234.7 3720.12     248 3721.26   259.1 3721.87   263.2 3723.73   271.3 3732.97
   279.6 3737.38   327.9 3743.42   345.3 3748.23   407.5 3760.95   453.4 3776.63
     470 3783.52   482.5 3786.92   503.6 3796.41   545.6 3811.64   558.5 3817.73
#Mann= 7 ,-1,0
       0      .1       0  225.14     .06       0   228.6    .045       0
     248     .06       0  295.14      .1       0  325.14     .06       0
  427.19      .1       0
Bank Sta=228.6,248
XS Rating Curve= 0 ,0
Exp/Cntr=0.3,0.1

Type RM Length L Ch R = 1 ,20690   ,253.7,243.4,237.2
XS GIS Cut Line= 4
  2200839.129703501642.7686790622200751.48099625501738.697005296
2200769.36200092 501861.64813429 2200767.2101448502102.024737095
#Sta/Elev= 30
       0  3772.7     6.6  3771.2    20.8 3764.12    35.8 3759.51    63.3 3747.28
    88.7 3739.32    95.4 3737.61   105.2 3737.47     123 3733.97   129.9 3733.77
   136.5 3731.25   168.8  3705.5   172.9  3702.8     181 3699.67 188.4883694.888
   206.8 3693.38216.96773694.306   225.4 3697.55   265.7 3696.15   277.7 3697.93
   309.7 3695.63   333.7 3695.27   349.7 3696.38   385.7  3694.5   405.7    3695
   437.7  3694.2   453.7 3698.59   469.7 3705.84   481.7 3711.99   494.6 3721.82
#Mann= 5 ,-1,0
       0      .1       0 188.488    .045       0216.9677      .1       0
  284.19     .06       0  374.19      .1       0
#XS Ineff= 2 , 0
                          230.28         3710.56
Permanent Ineff=
       F       F
Bank Sta=188.488,216.9677
XS Rating Curve= 0 ,0
Exp/Cntr(USF)=0,0
Exp/Cntr=0.3,0.1

Type RM Length L Ch R = 1 ,20446   ,318.5,328.8,340.4
XS GIS Cut Line= 4
2200655.68153279501612.172035657  2200571.293863501772.674074288
 2200598.0786175501961.1367112042200716.61499277502206.392965538
#Sta/Elev= 30
       0 3758.49    35.9 3747.92    73.4 3740.79     110 3730.75   150.3  3716.3
   181.3 3702.29   214.4 3701.92   230.3  3699.3   239.2 3695.79   254.6 3685.04
   274.5 3692.25   278.8    3692   286.9 3685.34   295.8 3683.75   331.3 3688.26
   363.7 3686.55   380.6 3687.66390.61633685.051410.8839 3685.09   425.1 3688.96
   442.8 3690.43   482.8 3688.22   496.1 3691.43   532.8 3717.58     547 3729.67
     550 3732.65   558.3  3746.9   567.2 3754.72   599.4 3771.41   644.1 3791.51
#Mann= 4 ,-1,0
       0      .1       0  301.33     .06       0390.6163    .045       0
410.8839      .1       0
#XS Ineff= 2 , 0
             276 3701.96
Permanent Ineff=
       F       F
Bank Sta=390.6163,410.8839
XS Rating Curve= 0 ,0
Exp/Cntr(USF)=0,0
Exp/Cntr=0.3,0.1

Type RM Length L Ch R = 1 ,20117   ,180.7,185.1,187.8
XS GIS Cut Line= 4
2200555.60102914501562.7053590142200417.08208569501678.666093101
2200319.43484494 501909.017640792200323.75136879502058.319369183
#Sta/Elev= 30
       0 3745.07    41.1  3731.1    56.6 3729.01    72.4 3725.48    80.9 3723.01
    93.2 3717.54   103.6 3714.75   119.2 3712.62   140.9 3714.03   176.6 3713.52
   187.7 3711.32   213.8 3698.35   228.9 3692.88   244.2 3691.11   265.9 3692.07
   270.3 3690.82   283.3 3678.45   296.2 3674.71   305.3 3669.86   309.4 3668.93
   331.1 3670.01   344.1  3674.4   370.2 3677.98   387.3 3689.55     405 3697.11
     479 3709.65     495  3711.5     523 3719.03   555.1 3723.11   580.2 3728.85
#Mann= 5 ,-1,0
       0      .1       0   305.3    .045       0   331.1      .1       0
  370.65     .06       0  510.84      .1       0
Bank Sta=305.3,331.1
XS Rating Curve= 0 ,0
Exp/Cntr=0.3,0.1

Type RM Length L Ch R = 1 ,19932   ,207.6,203.7,200.4
XS GIS Cut Line= 3
2200362.40825404501496.7788098752200146.81351414501818.861639932
2200171.25340368501994.305132728
#Sta/Elev= 30
       0 3730.88     5.3 3729.92    16.3 3730.17    42.3 3725.58    94.2    3713
   119.1 3710.84   137.4 3707.15   164.1 3704.51   186.4 3700.84   207.5  3694.5
   226.3 3684.47   234.1  3679.5   248.5 3673.41     270 3667.38   290.2 3666.13
   304.93662.409   313.2 3661.69   331.83662.164   351.9 3669.26   363.6 3675.39
   380.7 3679.89   398.1 3682.94   410.1 3686.36   433.4  3691.1   454.4 3696.42
   478.8 3704.42   490.9 3707.37   511.1 3715.21   551.5 3727.52   564.7 3732.63
#Mann= 5 ,-1,0
       0      .1       0   304.9    .045       0   331.8      .1       0
     350     .06       0  457.58      .1       0
Bank Sta=304.9,331.8
XS Rating Curve= 0 ,0
Exp/Cntr(USF)=0,0
Exp/Cntr=0.3,0.1

Type RM Length L Ch R = 1 ,19729   ,176,175.1,176.8
XS GIS Cut Line= 4
2200195.21731091501414.9546212362200091.31808741 501487.44917501
2199986.70496974501733.7662774972199963.39803872501942.695388542
#Sta/Elev= 30
       0 3743.09    37.9 3733.13    52.6 3732.56    62.2 3734.09    80.8 3729.88
   106.1 3720.06   132.9 3714.47   150.3 3709.24   167.7  3701.7   189.4 3697.31
   216.6 3688.82   219.8 3687.73   232.9 3679.44   258.9 3658.14     272 3656.14
     285 3651.55   298.1 3650.84   313.4 3651.79   328.7 3655.91     350 3666.65
   376.3 3669.33   425.9 3678.06     438 3679.33   478.2 3690.69   494.3 3692.65
   518.5 3698.24   551.8 3709.25   574.8 3719.18     588 3723.02   604.5 3730.36
#Mann= 5 ,-1,0
       0      .1       0  236.69     .06       0     285    .045       0
   313.4     .06       0   454.3      .1       0
Bank Sta=285,313.4
XS Rating Curve= 0 ,0
Exp/Cntr=0.3,0.1

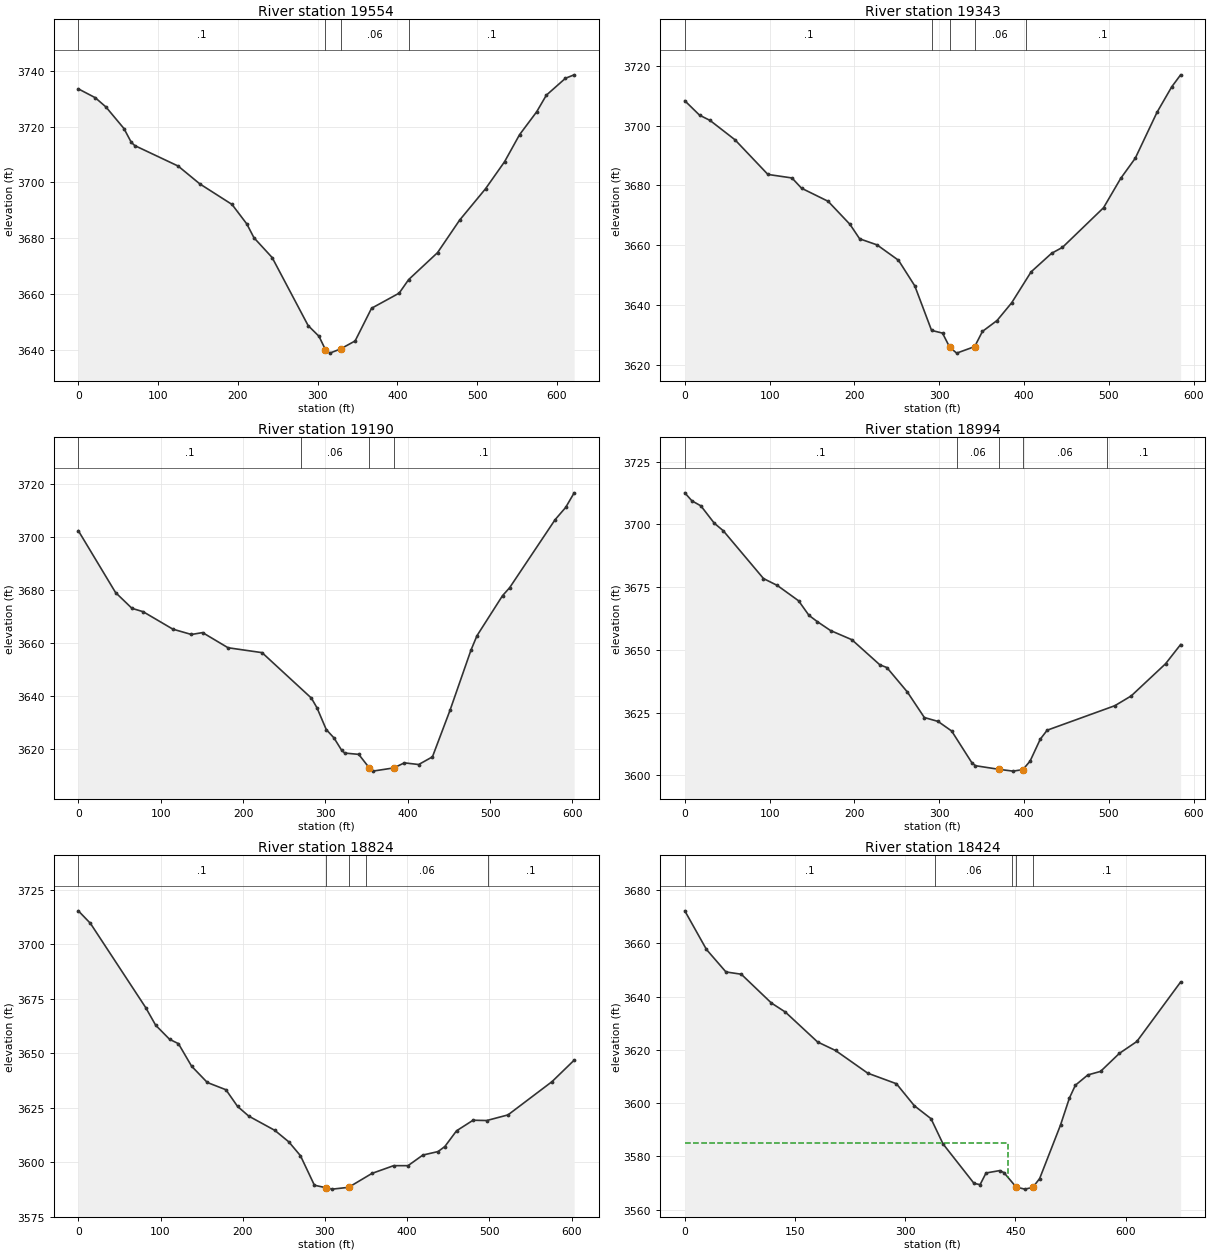
Type RM Length L Ch R = 1 ,19554   ,212.2,210.7,208.6
XS GIS Cut Line= 3
2200002.09075693501322.6065020462199826.69677657501653.538540459
2199810.15017465501900.082909077
#Sta/Elev= 30
       0 3733.51    21.2 3730.34    34.6 3727.02    57.2 3719.28    66.3 3714.37
    70.8 3713.16   125.1 3705.83   152.3 3699.43   192.7 3692.05   211.2 3685.07
   220.2 3680.11     243 3673.01   288.1 3648.62   301.7 3644.78   309.8 3639.98
   315.3 3638.74   328.7 3640.24     347 3643.11   367.6 3654.83   402.2 3660.25
   414.1 3665.11   450.3 3674.77     478 3686.43   510.5 3697.69   534.4  3707.4
   553.1 3717.05   574.6 3725.28   586.7 3731.23   610.7 3737.31   621.6 3738.54
#Mann= 4 ,-1,0
       0      .1       0   309.8    .045       0   328.7     .06       0
  414.54      .1       0
Bank Sta=309.8,328.7
XS Rating Curve= 0 ,0
Exp/Cntr(USF)=0,0
Exp/Cntr=0.3,0.1

Type RM Length L Ch R = 1 ,19343   ,155.8,152.9,155.1
XS GIS Cut Line= 3
2199857.53253402501280.5368056312199702.58437857501410.213437036
2199564.58182519501767.098563356
#Sta/Elev= 30
       0 3708.36    17.4 3703.54    29.8 3701.77    59.1 3695.32      98  3683.7
   126.4 3682.52   137.7 3679.08     169 3674.71   194.8 3666.98   206.2 3662.15
   226.7 3660.12     252 3654.97   271.2 3646.41     291  3631.5   303.9 3630.59
   312.4 3625.86   320.6 3623.89   341.8 3626.07     351 3631.16   368.2  3634.8
   385.4 3640.71   408.4  3651.1   432.5 3657.29   445.4  3659.3   493.8 3672.55
     514 3682.36   531.2 3689.12   556.9 3704.52   574.2 3713.02   584.7 3717.04
#Mann= 5 ,-1,0
       0      .1       0  292.05     .06       0   312.4    .045       0
   341.8     .06       0  402.05      .1       0
Bank Sta=312.4,341.8
XS Rating Curve= 0 ,0
Exp/Cntr=0.3,0.1

Type RM Length L Ch R = 1 ,19190   ,180.5,195.9,223
XS GIS Cut Line= 3
2199761.17876465501250.5275827582199526.47823808501441.585449429
2199423.67552809501722.838146558
#Sta/Elev= 30
       0 3702.51    45.2 3679.12    65.1 3673.15    78.7 3671.87   114.8 3665.27
   137.3 3663.26   150.9 3663.97   181.8 3658.24   223.1 3656.39     283  3639.2
   289.8 3635.53   301.1 3627.28   310.4 3624.16   319.7  3619.5   323.5 3618.41
   340.5 3617.92   353.3 3612.81   357.6 3611.58   383.1  3612.8   395.9 3614.71
   413.3 3614.08     430 3616.98   451.3 3634.55   476.8 3657.35   484.1  3662.8
   515.1 3677.93   523.7 3680.93     579 3706.69   591.8 3711.31   602.1 3716.83
#Mann= 4 ,-1,0
       0      .1       0     270     .06       0   353.3    .045       0
   383.1      .1       0
Bank Sta=353.3,383.1
XS Rating Curve= 0 ,0
Exp/Cntr(USF)=0,0
Exp/Cntr=0.3,0.1

Type RM Length L Ch R = 1 ,18994   ,181.2,170.5,153.4
XS GIS Cut Line= 4
2199718.54818641501189.7207420212199543.31967207501340.361005907
2199317.98002299 501363.720385672199248.26066663501469.937445547
#Sta/Elev= 30
       0 3712.54     8.4 3709.35      19 3707.34    34.8 3700.43    45.3 3697.47
    92.8 3678.41   109.1 3675.66   134.2 3669.55   146.4 3663.76   156.1  3661.3
   171.9  3657.7     197 3654.06     230 3644.06   238.3 3642.97   262.4 3633.26
   282.5 3623.07   298.6 3621.53   314.7  3617.7   338.8 3604.92   342.8 3603.89
   370.93602.421   387.1 3601.73   398.7 3602.33   407.2 3605.74   419.2 3614.46
   427.3 3618.02   507.2 3627.79   526.4 3631.67   566.9 3644.47   584.7 3652.14
#Mann= 5 ,-1,0
       0      .1       0  321.08     .06       0   370.9    .045       0
   398.7     .06       0  497.63      .1       0
Bank Sta=370.9,398.7
XS Rating Curve= 0 ,0
Exp/Cntr(USF)=0,0
Exp/Cntr=0.3,0.1

Type RM Length L Ch R = 1 ,18824   ,388.7,399.2,408
XS GIS Cut Line= 3
2199586.69166034500962.196572741 2199282.1964079501304.616397927
2199186.89471822501413.819427454
#Sta/Elev= 30
       0 3715.34    14.7 3709.59      82  3670.9    94.1 3662.83     111 3656.38
   121.8 3654.36   137.8 3644.03   156.9 3636.55   179.6 3633.21   193.7 3625.57
   207.4  3621.1   239.1 3614.56   256.1 3609.28   270.2 3602.96   287.2 3589.39
   301.4 3588.23   309.1  3587.6   328.8 3588.43   357.3 3594.83   383.6 3598.37
   401.1 3598.37   419.1 3603.23   437.6 3604.84   445.9 3607.16   460.1 3614.37
   480.2 3619.22   496.9 3619.09   522.7 3621.67   576.3 3636.95   603.2 3646.79
#Mann= 5 ,-1,0
       0      .1       0   301.4    .045       0   328.8      .1       0
     350     .06       0  498.22      .1       0
Bank Sta=301.4,328.8
XS Rating Curve= 0 ,0
Exp/Cntr=0.3,0.1

Type RM Length L Ch R = 1 ,18424   ,396.7,384.9,352.7
XS GIS Cut Line= 4
2199436.31665614500833.0945639622199120.28913388501054.055935813
2198973.10349951501078.7675563332198860.06700551501161.681032088
#Sta/Elev= 30
       0 3672.22    29.5 3657.71      56 3649.28    76.9 3648.42   117.9 3637.61
   136.8 3634.24   180.8 3622.99   205.2 3619.79   249.1 3611.27   288.1 3607.31
   312.5 3599.05   335.2 3594.19   351.6  3584.7   393.8 3569.89     402 3569.44
   410.1 3573.81   428.6  3574.7   434.4 3573.97451.13673568.515   462.8 3567.75
473.72263568.388   483.1 3571.73   511.5 3591.82   523.6 3601.94   531.7 3606.75
   548.7 3610.62     566 3611.94   591.6 3618.71   615.4 3623.17     675  3645.5
#Mann= 5 ,-1,0
       0      .1       0     340     .06       0  445.61      .1       0
451.1367    .045       0473.7226      .1       0
#XS Ineff= 2 , 0
          440.25 3585.08
Permanent Ineff=
       F       F
Bank Sta=451.1367,473.7226
XS Rating Curve= 0 ,0
Exp/Cntr=0.3,0.1

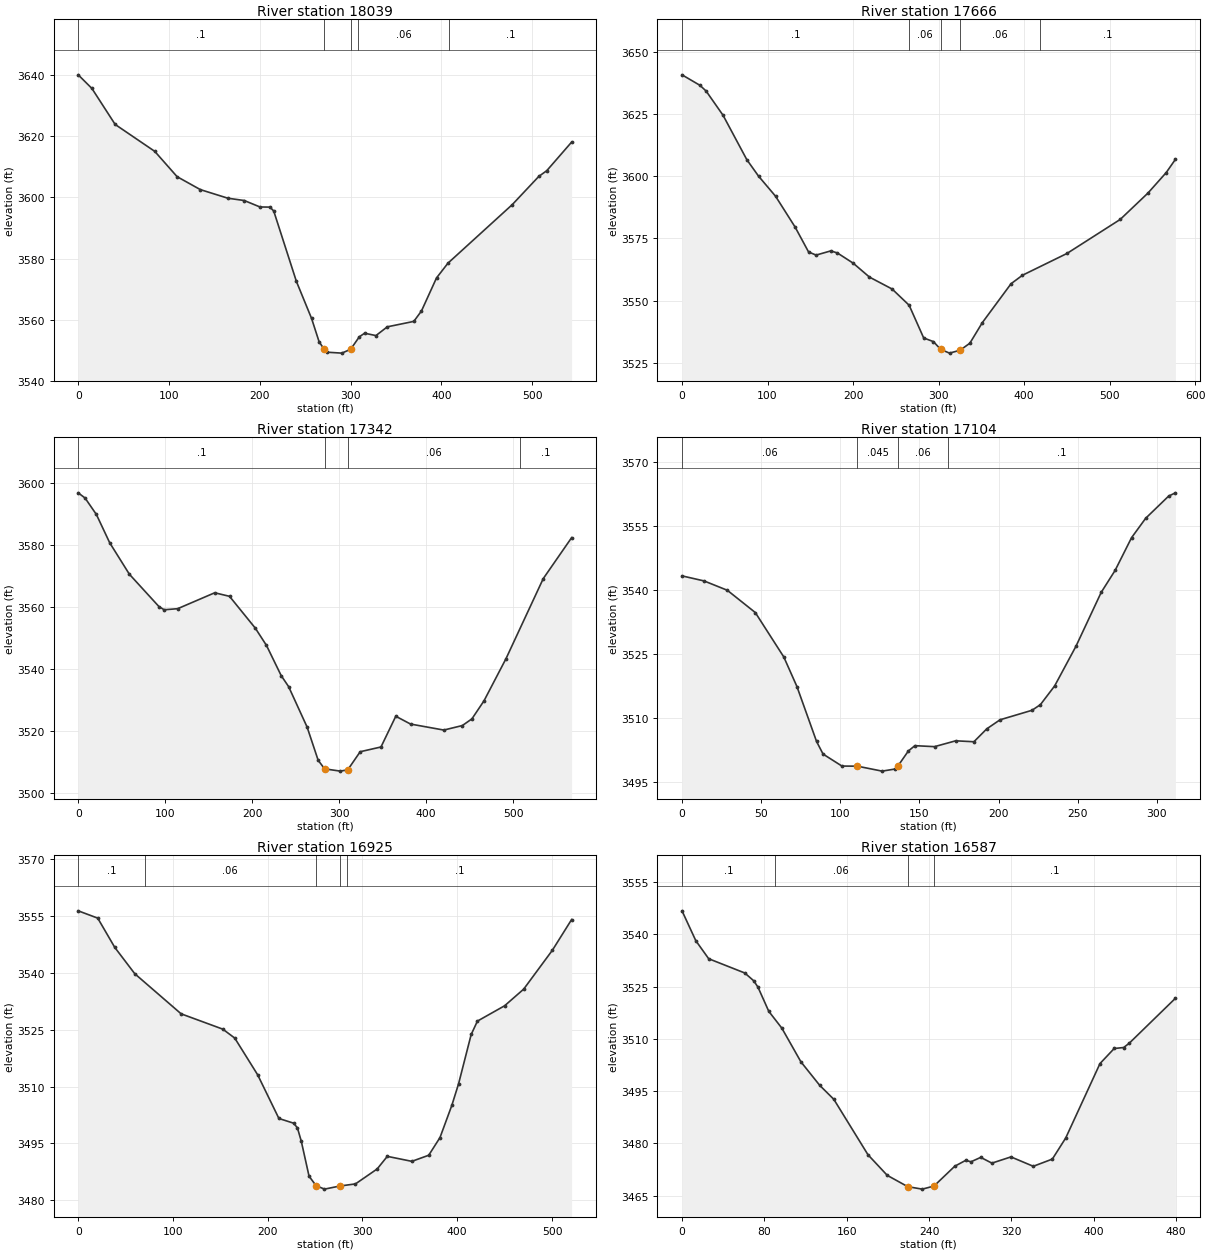
Type RM Length L Ch R = 1 ,18039   ,367.2,373.9,389.6
XS GIS Cut Line= 3
2199088.36712849500576.164522993 2198934.2355316500700.810075262
2198836.39547445501031.857939888
#Sta/Elev= 30
       0 3640.11    15.1 3635.65    40.7 3623.88    84.3 3615.08   108.9  3606.8
   134.5 3602.57   164.9 3599.75   182.9    3599   200.2 3596.89   211.1 3596.85
   215.3 3595.59   240.3 3572.54     257 3560.44   265.3  3552.8     271 3550.31
   274.2 3549.39   290.3 3549.09     300 3550.34   309.6 3554.43   315.4  3555.6
   327.9 3554.83   340.4 3557.69   369.6 3559.47     378 3562.86   394.6 3573.68
   407.2 3578.51   478.1 3597.68   507.3  3606.9     516 3608.75   543.4 3618.11
#Mann= 5 ,-1,0
       0      .1       0     271    .045       0     300      .1       0
  308.22     .06       0  408.22      .1       0
Bank Sta=271,300
XS Rating Curve= 0 ,0
Exp/Cntr(USF)=0,0
Exp/Cntr=0.3,0.1

Type RM Length L Ch R = 1 ,17666   ,314.5,323.5,328.1
XS GIS Cut Line= 4
2198928.48302933500340.1170990222198852.47877151500397.907980503
2198612.52173832500598.2080858822198501.20774937500725.320581607
#Sta/Elev= 30
       0 3640.84      21 3636.61    28.2  3634.3      48 3624.55    75.8 3606.68
    89.5 3600.06   109.4 3591.97   132.3 3579.54     148 3569.54   156.8 3568.29
     174 3569.98   181.7 3569.14   200.1 3565.05   219.2 3559.43   245.7 3554.63
   265.6  3548.1   282.6 3534.94     294 3533.46   302.5 3530.34   312.8 3528.83
   325.2    3530   336.6 3532.82   351.2 3541.11   384.8 3556.77   398.1 3560.17
   450.1 3568.93   512.4 3582.63   544.9 3593.26   566.2 3601.49     577 3606.83
#Mann= 5 ,-1,0
       0      .1       0  265.48     .06       0   302.5    .045       0
   325.2     .06       0  418.05      .1       0
Bank Sta=302.5,325.2
XS Rating Curve= 0 ,0
Exp/Cntr=0.3,0.1

Type RM Length L Ch R = 1 ,17342   ,256,237.6,220.7
XS GIS Cut Line= 4
2198721.35222738500163.2637377792198605.58386007500266.920381281
 2198330.4673264500365.1294951112198261.37629982500462.677984709
#Sta/Elev= 30
       0 3596.68     7.9    3595    20.9 3589.71    36.2 3580.61    58.8  3570.5
    92.8 3560.09    98.8 3559.06   114.3 3559.41   156.9 3564.53   173.9 3563.39
   203.6 3553.13   216.4 3547.59   233.3 3537.88   241.8 3534.36   263.1 3521.32
   275.8 3510.64   283.23507.895   301.3 3507.16   309.8 3507.59   324.1  3513.4
     348 3514.93     365 3524.81     382  3522.3   420.2 3520.37   441.5 3521.82
   452.5 3523.97   466.4 3529.78   491.7 3543.35   534.5 3569.09   567.1 3582.26
#Mann= 4 ,-1,0
       0      .1       0   283.2    .045       0   309.8     .06       0
  507.51      .1       0
Bank Sta=283.2,309.8
XS Rating Curve= 0 ,0
Exp/Cntr=0.3,0.1

Type RM Length L Ch R = 1 ,17104   ,159.1,179,211.6
XS GIS Cut Line= 4
2198353.04838326500118.2793364172198302.86581089500146.844233066
2198261.26997699500302.2920124062198218.73936842  500385.0644546
#Sta/Elev= 30
       0 3543.37    13.9 3542.19    28.6    3540    46.3 3534.77    64.3 3524.35
    72.6 3517.41      85 3504.53    89.1 3501.58     101 3498.77   110.8 3498.74
   126.4 3497.58   134.7 3498.08   136.4 3498.79     143 3502.31   147.1 3503.55
   159.5 3503.32   172.9 3504.69   184.4 3504.47   192.5 3507.49   200.9 3509.62
   221.1 3511.85   226.4 3513.17   235.4 3517.56   248.9 3526.89   264.8  3539.5
   273.6 3544.66     284 3552.34   292.9 3556.88   307.4 3562.08   311.7 3562.85
#Mann= 4 ,-1,0
       0     .06       0   110.8    .045       0   136.4     .06       0
  167.74      .1       0
Bank Sta=110.8,136.4
XS Rating Curve= 0 ,0
Exp/Cntr(USF)=0,0
Exp/Cntr=0.3,0.1

Type RM Length L Ch R = 1 ,16925   ,352.3,338.6,319.9
XS GIS Cut Line= 4
2198430.77806259 500012.559197952198227.69596088500106.125910119
2198137.79208148500086.9231397632197971.72556823500207.416449966
#Sta/Elev= 30
       0 3556.41    20.6 3554.48    38.6 3546.74    59.7 3539.79   108.6  3529.2
   152.6 3525.15   165.2 3522.79   189.4 3513.08   211.8 3501.55   227.2 3500.32
   231.3  3499.1   235.4 3495.56   243.6 3486.31     251 3483.81   259.9 3482.89
   276.3 3483.72   292.6 3484.27   315.5 3488.22   326.2 3491.55   352.1 3490.23
   369.9 3491.84   381.8 3496.52   394.3 3505.03   401.4 3510.71   414.7 3523.74
   421.3 3527.28     450 3531.33   470.1 3535.72   500.4    3546   520.7 3554.11
#Mann= 5 ,-1,0
       0      .1       0      70     .06       0     251    .045       0
   276.3     .06       0   283.6      .1       0
Bank Sta=251,276.3
XS Rating Curve= 0 ,0
Exp/Cntr=0.3,0.1

Type RM Length L Ch R = 1 ,16587   ,338.5,338.8,338.4
XS GIS Cut Line= 4
2198247.73050033 499689.261961632198127.10577233499760.296523675
2197958.23115313499905.046197277 2197856.3702717499962.678011766
#Sta/Elev= 30
       0 3546.79    13.4 3538.21    25.9 3533.03      61 3528.93    69.7 3526.68
    73.8 3524.86    84.3 3517.92      97 3513.08   115.5 3503.42   133.8 3496.65
   147.5 3492.64   180.7 3476.71   199.4  3470.8   219.3 3467.55   233.4 3466.84
   244.8 3467.72     265 3473.42   275.6  3475.1   280.8  3474.7   290.2 3475.96
   301.1 3474.31   319.6  3476.1   341.3  3473.4   359.8 3475.47   372.8 3481.53
   406.1 3502.91   419.9 3507.24   429.1 3507.52   434.5 3508.75   479.4 3521.67
#Mann= 4 ,-1,0
       0      .1       0      90     .06       0   219.3    .045       0
   244.8      .1       0
Bank Sta=219.3,244.8
XS Rating Curve= 0 ,0
Exp/Cntr(USF)=0,0
Exp/Cntr=0.3,0.1