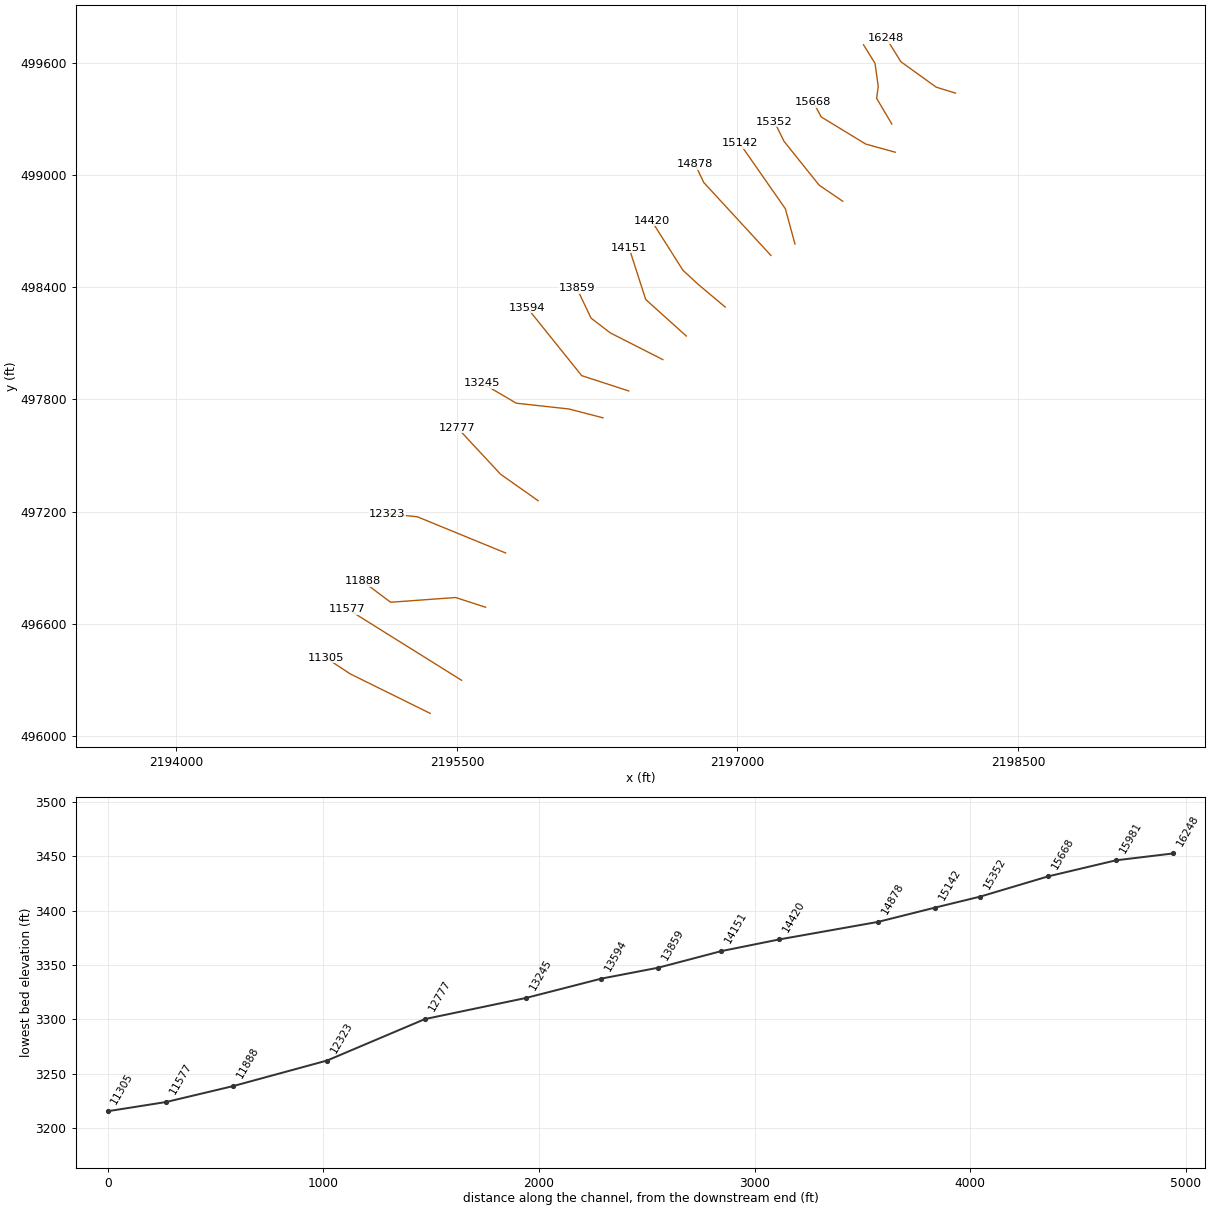
HEC-RAS study TEACK.prj: TEACK

--- TEACK.g01 (geometry) --- (continued)

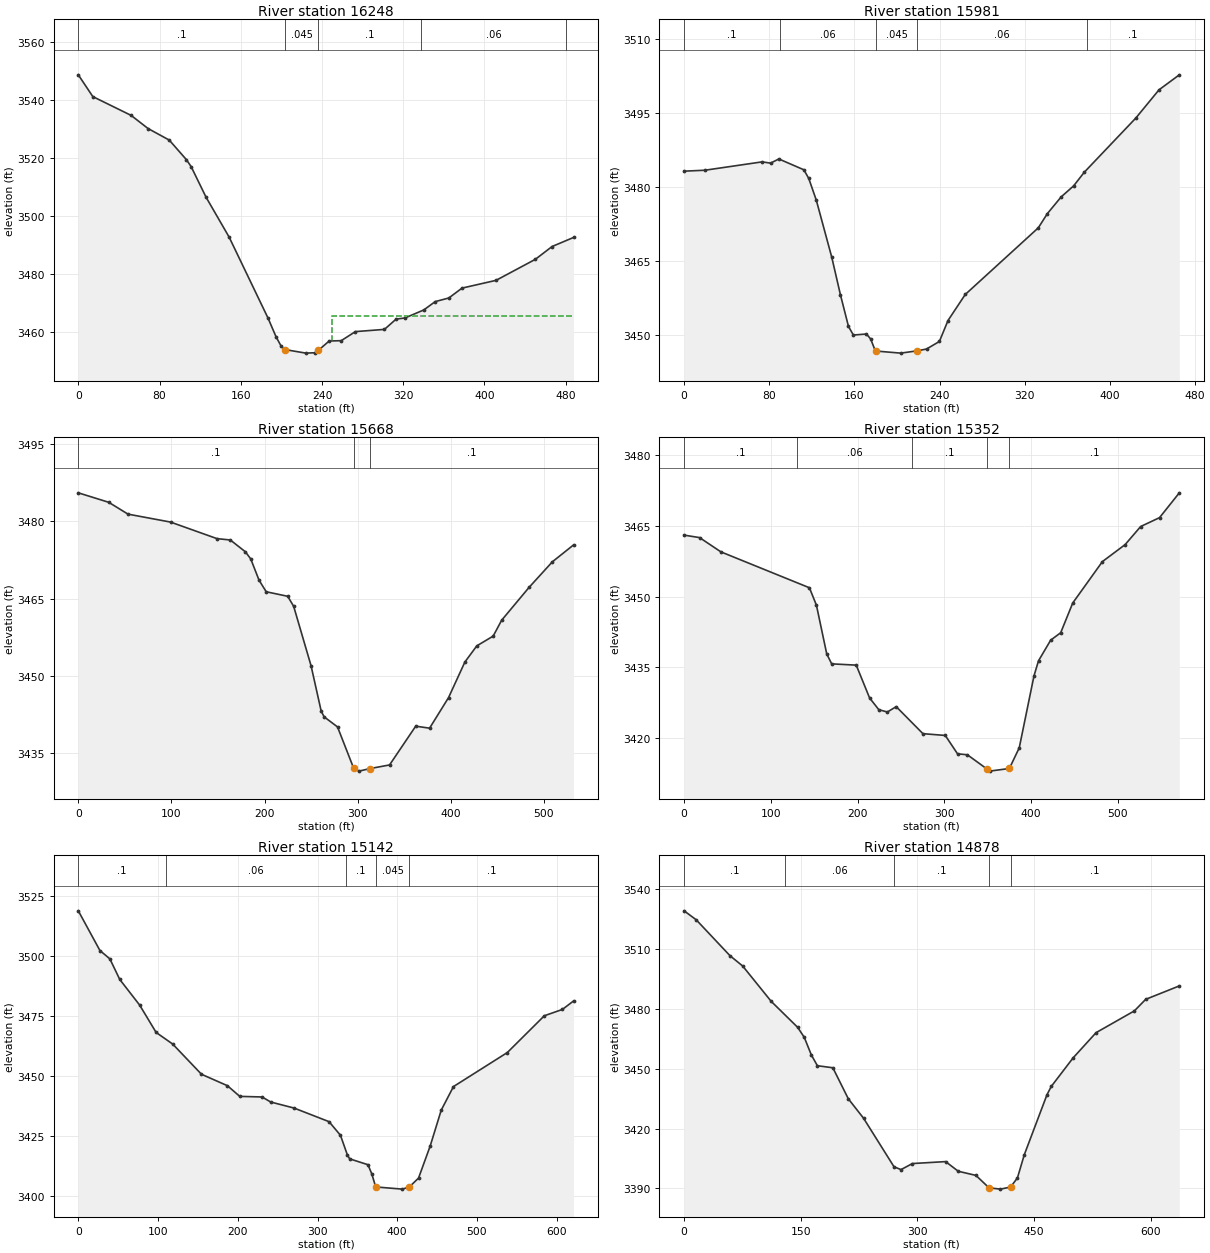
Type RM Length L Ch R = 1 ,16248   ,293.4,266.7,244.8
XS GIS Cut Line= 4
2198165.80885084499437.5885913772198062.77258406499469.456901716
2197874.05544773  499605.29258162197796.32653271499730.421633242
#Sta/Elev= 30
       0  3548.7    14.3 3541.18      52 3534.69    68.7 3530.15    89.6 3526.15
   106.4 3519.42   111.1 3517.01   125.8 3506.44   148.5 3492.67   186.9 3464.63
   194.8 3458.17   199.8 3454.96   203.2 3453.82   224.1 3452.57   232.7  3452.7
   236.33453.506   247.1 3456.76   258.9 3456.87   272.9    3460   301.5 3460.77
     313 3464.33   321.6  3464.7   340.2 3467.48   351.5 3470.37   364.9 3471.62
   377.9 3475.03   411.4 3477.71   450.1 3484.97   466.6  3489.4   487.7 3492.52
#Mann= 5 ,-1,0
       0      .1       0   203.2    .045       0   236.3      .1       0
  337.85     .06       0  480.37      .1       0
#XS Ineff= 2 , 0
                          249.95          3465.5
Permanent Ineff=
       F       F
Bank Sta=203.2,236.3
XS Rating Curve= 0 ,0
Exp/Cntr=0.3,0.1

Type RM Length L Ch R = 1 ,15981   ,282.4,313.7,335.3
XS GIS Cut Line= 6
2197825.54395233499272.4365126472197765.23158833499374.297394071
2197744.13528919499409.5890581252197752.86382117499473.307341578
 2197735.7455437499596.7830034962197674.09290495499695.963335408
#Sta/Elev= 30
       0  3483.2    19.5 3483.39    73.3 3485.09    81.2 3484.83      89 3485.68
   112.5 3483.48   117.1 3481.72   124.2 3477.29   138.7 3465.71   146.8 3458.12
   154.4 3451.65     159  3449.9   171.2  3450.1   175.2 3449.12   179.3 3446.85
   180.5 3446.64   203.5 3446.22   218.7 3446.68   227.7 3447.05   239.8 3448.59
   247.9 3452.85   264.1 3458.14   332.7 3471.68   341.3 3474.59   354.2 3477.97
   365.9 3480.21   375.9 3482.98   424.3 3493.99   446.1 3499.73   465.2 3502.78
#Mann= 5 ,-1,0
       0      .1       0      90     .06       0   180.5    .045       0
   218.7     .06       0  378.46      .1       0
Bank Sta=180.5,218.7
XS Rating Curve= 0 ,0
Exp/Cntr(USF)=0,0
Exp/Cntr=0.3,0.1

Type RM Length L Ch R = 1 ,15668   ,317,315.1,311.6
XS GIS Cut Line= 4
2197843.67219529499121.6637503132197686.15537775499165.214532202
2197448.06106142499310.1435690652197405.50624267499389.110991729
#Sta/Elev= 30
       0 3485.54    32.7  3483.7    53.4  3481.4    99.1 3479.86   148.9 3476.65
   163.3 3476.38   179.4  3474.1   185.2 3472.71   194.1 3468.59   201.8 3466.33
   224.9 3465.45   231.3 3463.51     250 3451.96   260.9 3443.13   264.1 3442.03
   278.4 3440.09   295.8 3432.04   301.5  3431.5   313.1 3431.99   334.3  3432.7
   362.4 3440.23   377.3 3439.84   397.7 3445.79   415.2 3452.68     428 3455.82
   445.6 3457.72   454.7  3460.8   484.1 3467.17   509.2 3472.15   531.9 3475.42
#Mann= 3 ,-1,0
       0      .1       0   295.8    .045       0   313.1      .1       0
Bank Sta=295.8,313.1
XS Rating Curve= 0 ,0
Exp/Cntr=0.3,0.1

Type RM Length L Ch R = 1 ,15352   ,211.5,210.9,209.2
XS GIS Cut Line= 4
2197563.35625343498859.6124707012197437.15218408498945.397889667
2197249.09159232499179.8644271062197197.01873767499285.638757529
#Sta/Elev= 30
       0 3463.05    17.8 3462.53    42.5 3459.49   144.5 3451.87   152.6 3448.16
   164.5  3437.8   170.2  3435.7   198.5 3435.43   213.9 3428.46   224.5 3425.97
   234.4 3425.47   244.6 3426.61   275.4 3420.87   301.2 3420.49   315.3 3416.59
   326.7 3416.38   349.5 3413.33   352.3 3412.91   375.1 3413.47   386.5 3417.87
   403.5 3433.16   408.7 3436.35   422.7 3440.73   434.3 3442.32   448.2 3448.64
   482.4 3457.43   508.6 3461.04   526.5 3464.88   548.3 3466.77   571.1 3472.04
#Mann= 5 ,-1,0
       0      .1       0     130     .06       0   262.6      .1       0
   349.5    .045       0   375.1      .1       0
Bank Sta=349.5,375.1
XS Rating Curve= 0 ,0
Exp/Cntr=0.3,0.1

Type RM Length L Ch R = 1 ,15142   ,264.4,263.6,267.5
XS GIS Cut Line= 3
 2197307.7086902498631.0040055212197256.21035152498819.540296286
2197012.68430928499168.681575481
#Sta/Elev= 30
       0 3518.82    27.1 3502.27    39.6 3498.77      52 3490.19    76.9 3479.52
    97.6 3468.09   118.4 3463.24   154.5 3450.64     187 3445.88   202.5 3441.42
   230.5 3441.17   241.3 3439.07   270.6 3436.55   314.5 3430.87   328.8 3425.19
   337.4 3417.06   340.3 3415.37   363.3 3412.91   368.1 3409.07     373 3403.64
   406.4 3402.73     415  3403.6   426.7 3407.32   441.3 3420.69   455.2 3435.69
   470.5  3445.5   538.1 3459.71   584.5 3475.05   607.1 3477.68   621.1 3481.21
#Mann= 5 ,-1,0
       0      .1       0     110     .06       0  335.44      .1       0
     373    .045       0     415      .1       0
Bank Sta=373,415
XS Rating Curve= 0 ,0
Exp/Cntr(USF)=0,0
Exp/Cntr=0.3,0.1

Type RM Length L Ch R = 1 ,14878   ,454.9,457.9,452.9
XS GIS Cut Line= 3
2197179.02519412498569.7900260692196819.51133021498960.323970756
2196774.45662113499056.356844827
#Sta/Elev= 30
       0 3529.25    15.5 3524.77      59 3506.74    75.3 3501.58     112 3483.84
     146 3470.82   154.5 3465.81   163.7 3456.91   171.4 3451.55   191.3 3450.52
   211.2 3434.95   230.9 3425.14     270 3400.83     279 3399.44   293.6 3402.47
   336.3 3403.45   352.6  3398.6   375.3 3396.53   392.2 3390.28   406.9 3389.64
   419.9 3390.69   428.7 3395.28   437.5 3406.88   466.7    3437   472.2 3441.16
   500.3 3455.48   529.8 3468.13   579.1 3479.06   593.6 3484.84   636.9 3491.59
#Mann= 5 ,-1,0
       0      .1       0     130     .06       0     270      .1       0
   392.2    .045       0   419.9      .1       0
Bank Sta=392.2,419.9
XS Rating Curve= 0 ,0
Exp/Cntr=0.3,0.1

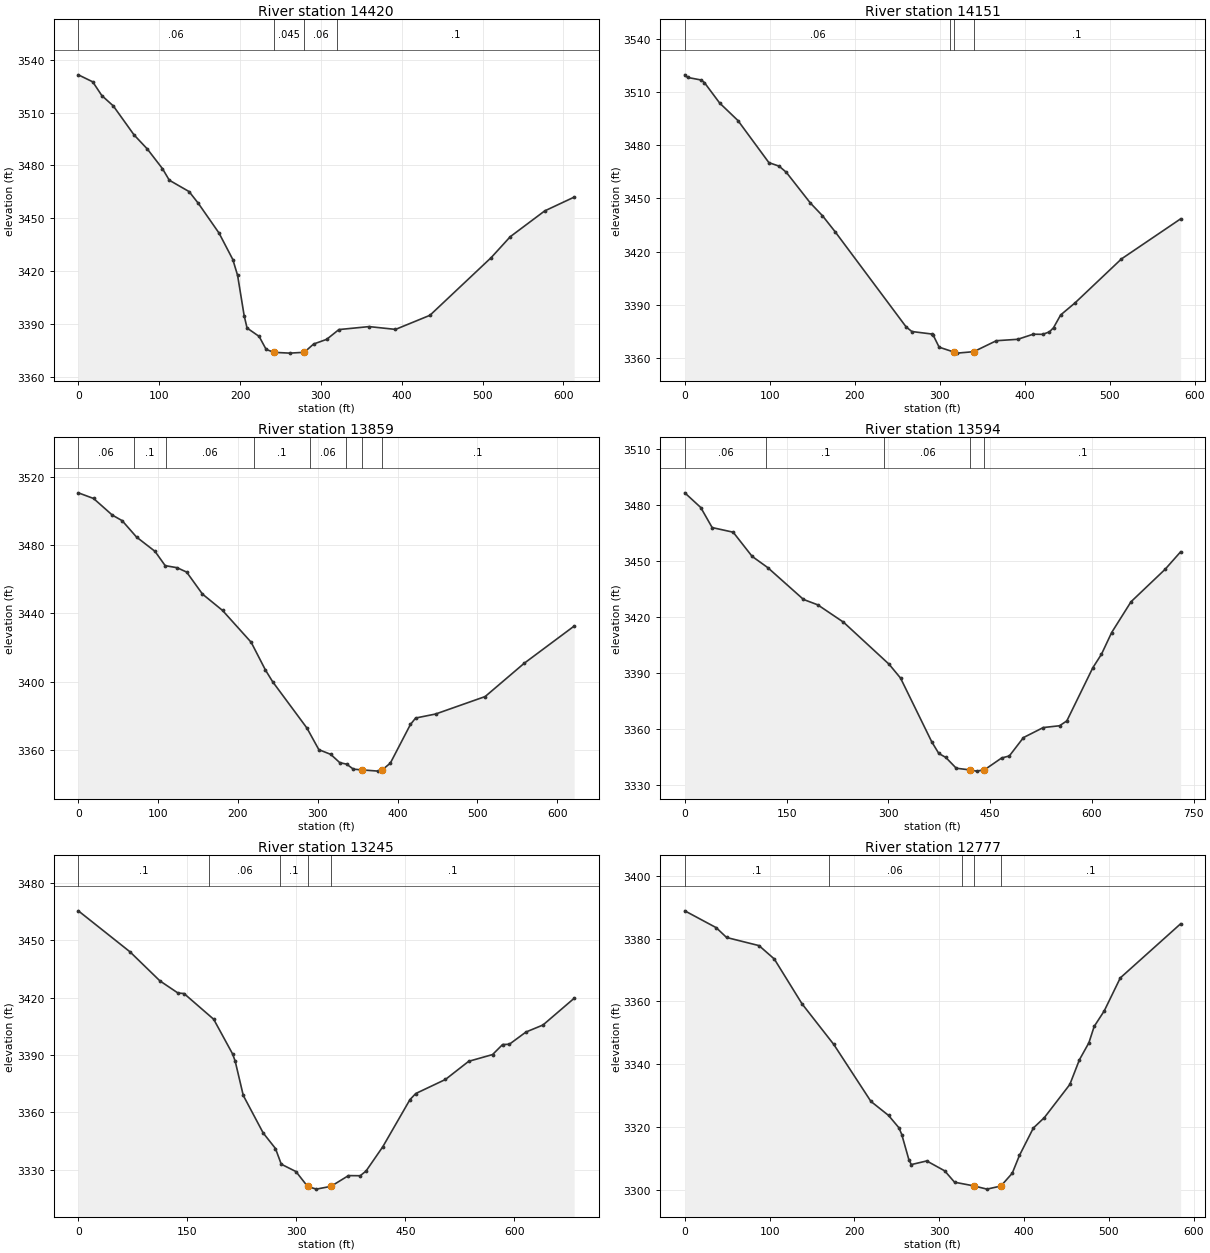
Type RM Length L Ch R = 1 ,14420   ,277,269.1,252.8
XS GIS Cut Line= 4
2196934.36155389 498294.303740032196789.77702748498415.545084677
2196708.07764426498491.2652364592196540.51300912498755.899233891
#Sta/Elev= 30
       0 3531.37    17.8  3527.4    29.1 3519.58    43.3 3513.71    68.9 3497.31
    85.4 3489.27   104.1 3478.14   112.5 3471.61     137 3465.15   148.4  3458.5
     174 3441.64   191.1 3426.61     197 3417.61   205.1 3394.82   208.7 3387.77
   223.6 3383.02   232.3 3375.65   241.9 3373.97   261.7 3373.53   279.4    3374
   291.1 3378.71   307.2 3381.35   322.3 3386.89   359.7 3388.58   392.3 3386.99
   434.9 3394.98   510.7 3427.72   534.3 3439.58   576.9  3454.2   613.3 3462.01
#Mann= 4 ,-1,0
       0     .06       0   241.9    .045       0   279.4     .06       0
  320.08      .1       0
Bank Sta=241.9,279.4
XS Rating Curve= 0 ,0
Exp/Cntr=0.3,0.1

Type RM Length L Ch R = 1 ,14151   ,278.9,292.3,299.8
XS GIS Cut Line= 3
2196726.62103888498139.0440277532196509.58336747498334.377932023
2196420.21491454498611.420136117
#Sta/Elev= 30
       0 3519.72     3.2 3518.26    19.4 3516.78    23.1 3515.32      41 3503.81
    62.5 3493.94    98.9  3470.2   110.9 3468.22   119.4 3464.74   147.7 3447.41
   161.9 3440.27   176.6 3431.36   260.3 3377.56     267 3374.97   290.2 3373.57
   292.2 3372.83   299.1 3366.14     316 3363.46   320.2 3362.78   339.8  3363.6
   366.4 3369.78   391.6 3370.58   409.7 3373.45     421 3373.38   428.8 3374.77
   433.6 3377.08     442  3384.3   458.9  3391.1   513.5  3415.9   583.1  3438.5
#Mann= 4 ,-1,0
       0     .06       0  311.99      .1       0     316    .045       0
   339.8      .1       0
Bank Sta=316,339.8
XS Rating Curve= 0 ,0
Exp/Cntr(USF)=0,0
Exp/Cntr=0.3,0.1

Type RM Length L Ch R = 1 ,13859   ,267.1,264.3,258
XS GIS Cut Line= 4
2196601.15855847498013.0802368182196320.63292413498155.641026155
2196217.22085716498234.7959416112196141.52398475 498393.92052098
#Sta/Elev= 30
       0 3510.69    19.1 3507.37    42.5 3497.66    54.9 3494.37    72.9 3484.77
      96  3476.4   108.8 3468.01   123.8 3466.79   135.7 3464.22   155.5 3451.34
   180.6 3441.77   216.5 3423.09   234.4 3406.82   243.4 3399.97   286.4 3372.78
   301.3 3360.13   316.1 3357.41   327.5 3352.53   336.1 3351.64   344.6 3348.71
   355.5 3348.28   375.7 3347.56   380.7 3348.32   390.8 3352.22     416  3374.9
   422.5 3378.68   447.5 3381.03   509.6 3391.27   558.5 3410.77   621.1 3432.58
#Mann= 8 ,-1,0
       0     .06       0      70      .1       0     110     .06       0
     220      .1       0     290     .06       0  334.67      .1       0
   355.5    .045       0   380.7      .1       0
Bank Sta=355.5,380.7
XS Rating Curve= 0 ,0
Exp/Cntr=0.3,0.1

Type RM Length L Ch R = 1 ,13594   ,332.2,349,359.2
XS GIS Cut Line= 3
2196418.50662594 497845.644955962196167.24341159497927.356570383
2195875.12439003498290.973254565
#Sta/Elev= 30
       0 3486.36    23.5 3478.51    40.3 3467.78    71.3  3465.3    99.2 3452.37
   122.1  3446.4   174.9 3429.33   195.9 3426.45   233.8 3417.18     301 3394.68
   317.9 3387.27     364 3353.09   374.3 3346.94   384.6 3344.82     400 3339.05
   420.5 3338.14   429.9  3337.5   441.6 3338.21   466.9 3344.54   478.2 3345.61
     499 3355.44   528.2 3360.81   552.2 3361.77   562.9 3364.35   601.2 3392.78
     614 3400.06     629 3411.65   657.5  3428.1   707.8 3445.47   730.6 3454.82
#Mann= 5 ,-1,0
       0     .06       0     120      .1       0  294.22     .06       0
   420.5    .045       0   441.6      .1       0
Bank Sta=420.5,441.6
XS Rating Curve= 0 ,0
Exp/Cntr(USF)=0,0
Exp/Cntr=0.3,0.1

Type RM Length L Ch R = 1 ,13245   ,486.5,468.8,457.6
XS GIS Cut Line= 4
2196280.96680598497702.0622038412196099.03603503497749.153600231
2195817.89184483497780.0344855962195635.15047556497886.877048668
#Sta/Elev= 30
       0 3465.39    71.1 3443.94   112.4 3428.69   137.2 3422.36   145.4 3422.12
   186.3 3408.64   212.3  3390.5   215.9 3386.68     227 3368.78   254.4 3349.15
   271.3 3341.01   279.3  3332.8   299.5 3328.95   315.6 3321.13   327.6 3319.75
   347.7 3321.21   371.8 3326.83     388 3326.76     396 3329.23     419 3341.91
   456.4 3366.59   464.4 3369.78   505.2 3377.13   537.2 3386.63   570.1 3390.17
   583.9 3395.42   593.2 3395.56   616.1 3401.97   639.5 3405.64   682.4 3419.62
#Mann= 5 ,-1,0
       0      .1       0     180     .06       0  277.93      .1       0
   315.6    .045       0   347.7      .1       0
Bank Sta=315.6,347.7
XS Rating Curve= 0 ,0
Exp/Cntr=0.3,0.1

Type RM Length L Ch R = 1 ,12777   ,442.6,453.6,459.9
XS GIS Cut Line= 3
2195934.37914466497258.7336644212195733.15346735497400.618324542
 2195502.7557223497648.374884958
#Sta/Elev= 30
       0 3388.82      37 3383.47    49.3 3380.34    87.5 3377.76   105.5 3373.51
   138.2 3359.25   175.6 3346.35   219.4 3328.23   240.2 3323.77   252.4 3319.85
   255.8 3317.68   264.3 3309.56   267.1 3308.15   285.2  3309.3   306.4 3306.15
     318 3302.54   340.7 3301.37   356.2 3300.34   372.6 3301.32     386 3305.39
   394.5 3311.06   410.9 3319.77   423.9 3323.09   453.9 3333.62   465.2 3341.47
   476.4 3346.89   482.6 3352.07   494.4 3356.98   513.4  3367.5   584.5  3384.7
#Mann= 5 ,-1,0
       0      .1       0     170     .06       0  326.22      .1       0
   340.7    .045       0   372.6      .1       0
Bank Sta=340.7,372.6
XS Rating Curve= 0 ,0
Exp/Cntr(USF)=0,0
Exp/Cntr=0.3,0.1

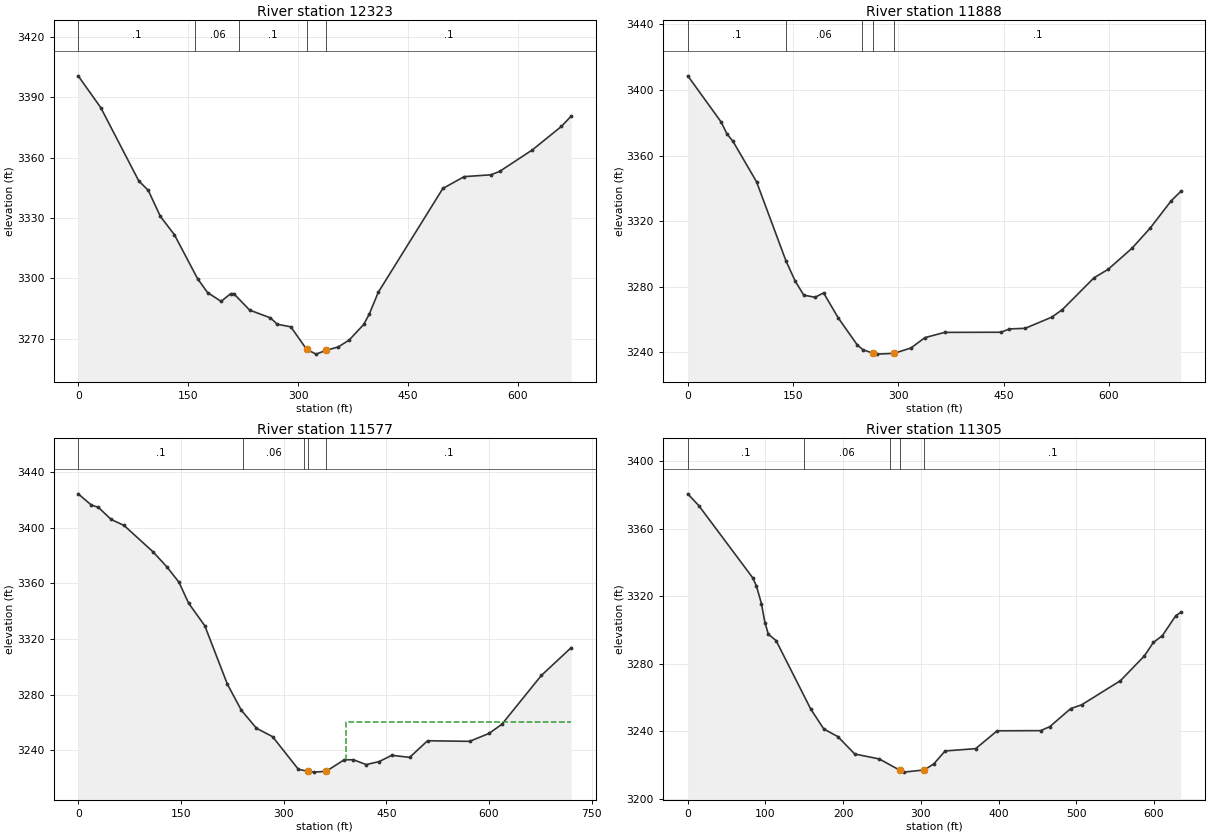
Type RM Length L Ch R = 1 ,12323   ,422.1,435,440.3
XS GIS Cut Line= 3
2195760.65377689496979.4021534222195288.36671247497172.956080065
2195126.94801253497190.135051643
#Sta/Elev= 30
       0 3400.74    30.8 3384.91    82.7 3348.44    95.6 3343.77   112.1 3330.82
   131.3 3321.68   162.9 3299.81   176.5 3292.91     195 3288.51     208 3292.31
   212.3 3292.35     234 3284.17   262.4 3280.29   271.6 3277.14   290.2 3275.84
   311.8  3264.6   324.7 3262.26   337.7 3264.08     355 3265.86   369.7 3269.25
   389.6 3277.01   397.3 3282.26   409.5 3293.03   497.6 3344.69   526.7 3350.58
   562.9 3351.48     575 3353.16   619.9 3363.92   659.4 3375.58   672.7 3380.68
#Mann= 5 ,-1,0
       0      .1       0     160     .06       0     220      .1       0
   311.8    .045       0   337.7      .1       0
Bank Sta=311.8,337.7
XS Rating Curve= 0 ,0
Exp/Cntr=0.3,0.1

Type RM Length L Ch R = 1 ,11888   ,327.1,311.2,302.3
XS GIS Cut Line= 4
 2195653.2633808496689.3705369772195493.42875007496741.387608772
2195145.69450483496716.0701158752194997.29935874496827.226441387
#Sta/Elev= 30
       0 3408.64    47.4 3380.52    55.8  3373.2    64.4 3368.62    97.9 3344.02
     140 3295.53     153 3283.38   165.2 3274.78   181.4 3273.51   193.4 3276.19
   214.3 3260.93   241.5 3244.35   249.6 3241.45   264.4  3239.3   269.6  3238.8
   293.7 3239.28   317.7 3242.51   337.7 3248.86   365.9 3252.07   446.1 3252.16
   458.1 3254.17   480.7 3254.57   518.6  3261.4   533.6 3265.99   578.6 3285.38
   598.7 3290.54   632.9 3303.48   658.7 3315.76   688.6  3332.4   702.2 3338.11
#Mann= 5 ,-1,0
       0      .1       0     140     .06       0  248.09      .1       0
   264.4    .045       0   293.7      .1       0
Bank Sta=264.4,293.7
XS Rating Curve= 0 ,0
Exp/Cntr=0.3,0.1

Type RM Length L Ch R = 1 ,11577   ,269.7,271.6,273.2
XS GIS Cut Line= 2
2195524.98059481496298.924797762 2194914.4132537496680.245665069
#Sta/Elev= 30
       0 3424.54    19.4 3416.37    29.2 3414.94    48.1 3406.09      67 3401.76
   109.4 3382.75     130 3371.67   147.1 3360.94   161.3 3345.76   184.9 3329.53
   217.9 3287.44   238.3 3268.69   260.3 3255.77   283.9 3249.69   321.5 3226.21
   335.8 3224.67   344.8 3224.15   362.2 3224.76   388.3    3233   401.8 3233.06
   420.7 3229.58   439.5 3231.76     458 3236.27   484.1 3234.78   510.2 3246.75
   571.6 3246.31   599.9 3252.01   618.7 3258.58   676.3 3293.73   719.9 3313.76
#Mann= 5 ,-1,0
       0      .1       0     240     .06       0     330      .1       0
   335.8    .045       0   362.2      .1       0
#XS Ineff= 2 , 0
                          390.85          3260.3
Permanent Ineff=
       F       F
Bank Sta=335.8,362.2
XS Rating Curve= 0 ,0
Exp/Cntr(USF)=0,0
Exp/Cntr=0.3,0.1

Type RM Length L Ch R = 1 ,11305   ,434.2,433.8,433.1
XS GIS Cut Line= 3
2195357.20818792 496122.055043522194929.56082002496333.141940588
2194798.00504056496419.860894159
#Sta/Elev= 30
       0 3380.73    14.5 3373.54    83.7 3330.84    88.4 3325.97    94.8  3315.6
    99.3 3304.31   103.7 3297.45   113.6 3293.72   158.4 3252.93   175.1 3241.23
     193 3236.78   214.9 3226.41   246.5 3223.47   273.3 3216.67   277.9 3215.66
   304.5 3216.96   316.7 3220.57   331.2 3228.22   370.5 3229.58   398.2 3240.17
   454.1 3240.27     466 3242.65   492.9 3253.37   506.8 3255.55   556.9 3269.92
   587.7  3284.6   599.2 3292.57   610.8  3296.6   628.1 3308.45   634.5 3310.45
#Mann= 5 ,-1,0
       0      .1       0     150     .06       0     260      .1       0
   273.3    .045       0   304.5      .1       0
Bank Sta=273.3,304.5
XS Rating Curve= 0 ,0
Exp/Cntr=0.3,0.1