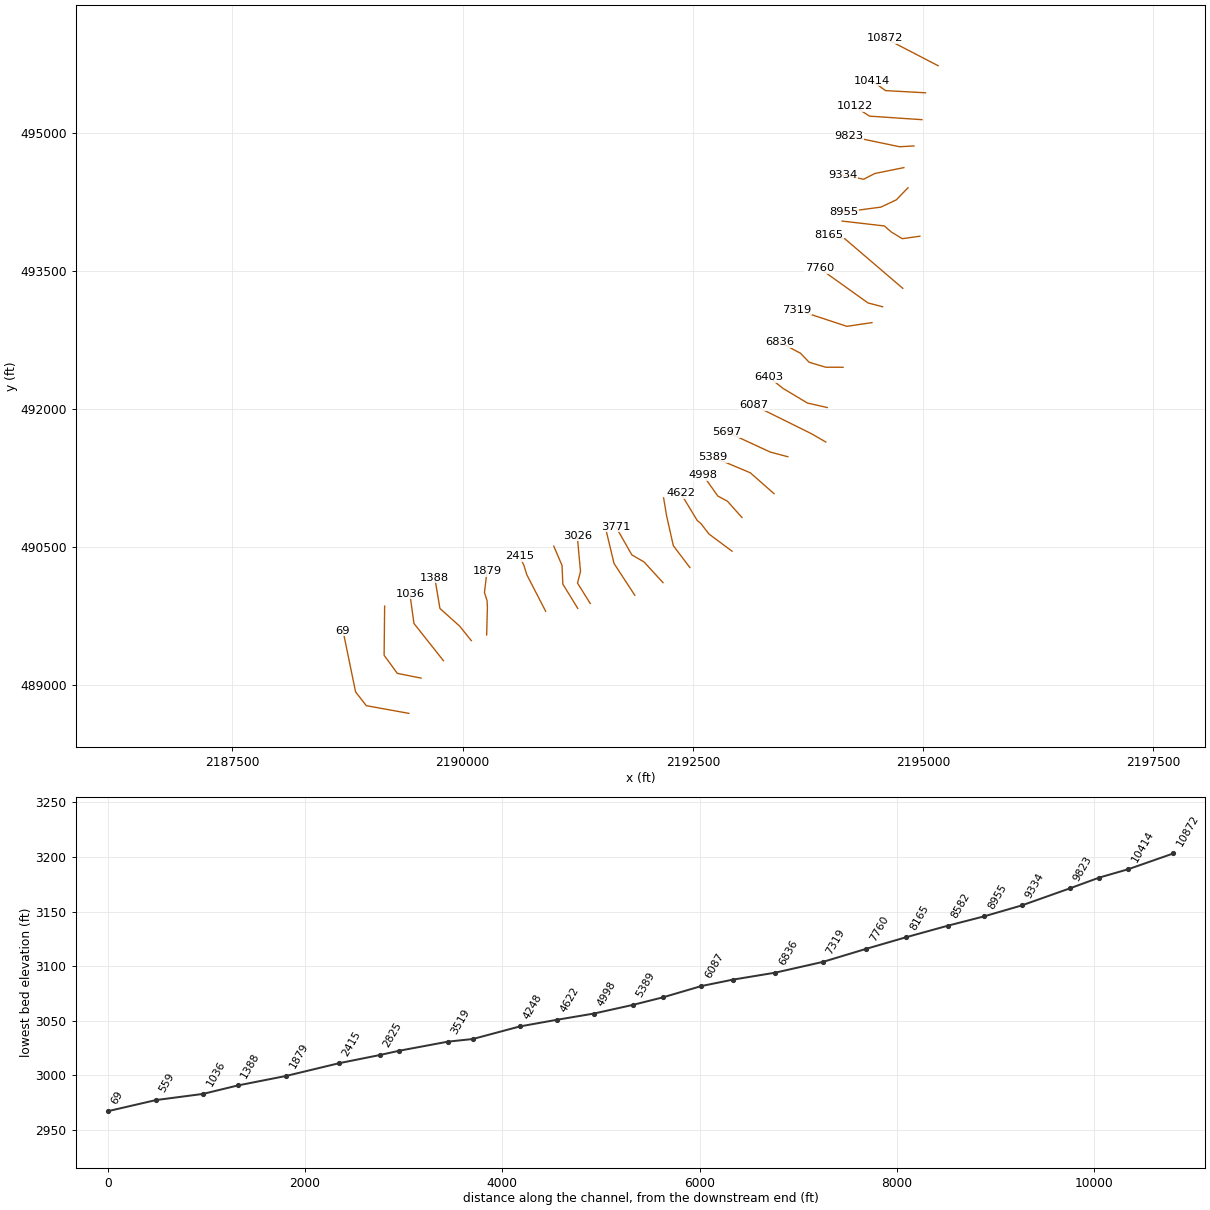
HEC-RAS study TEACK.prj: TEACK

--- TEACK.g01 (geometry) --- (continued)

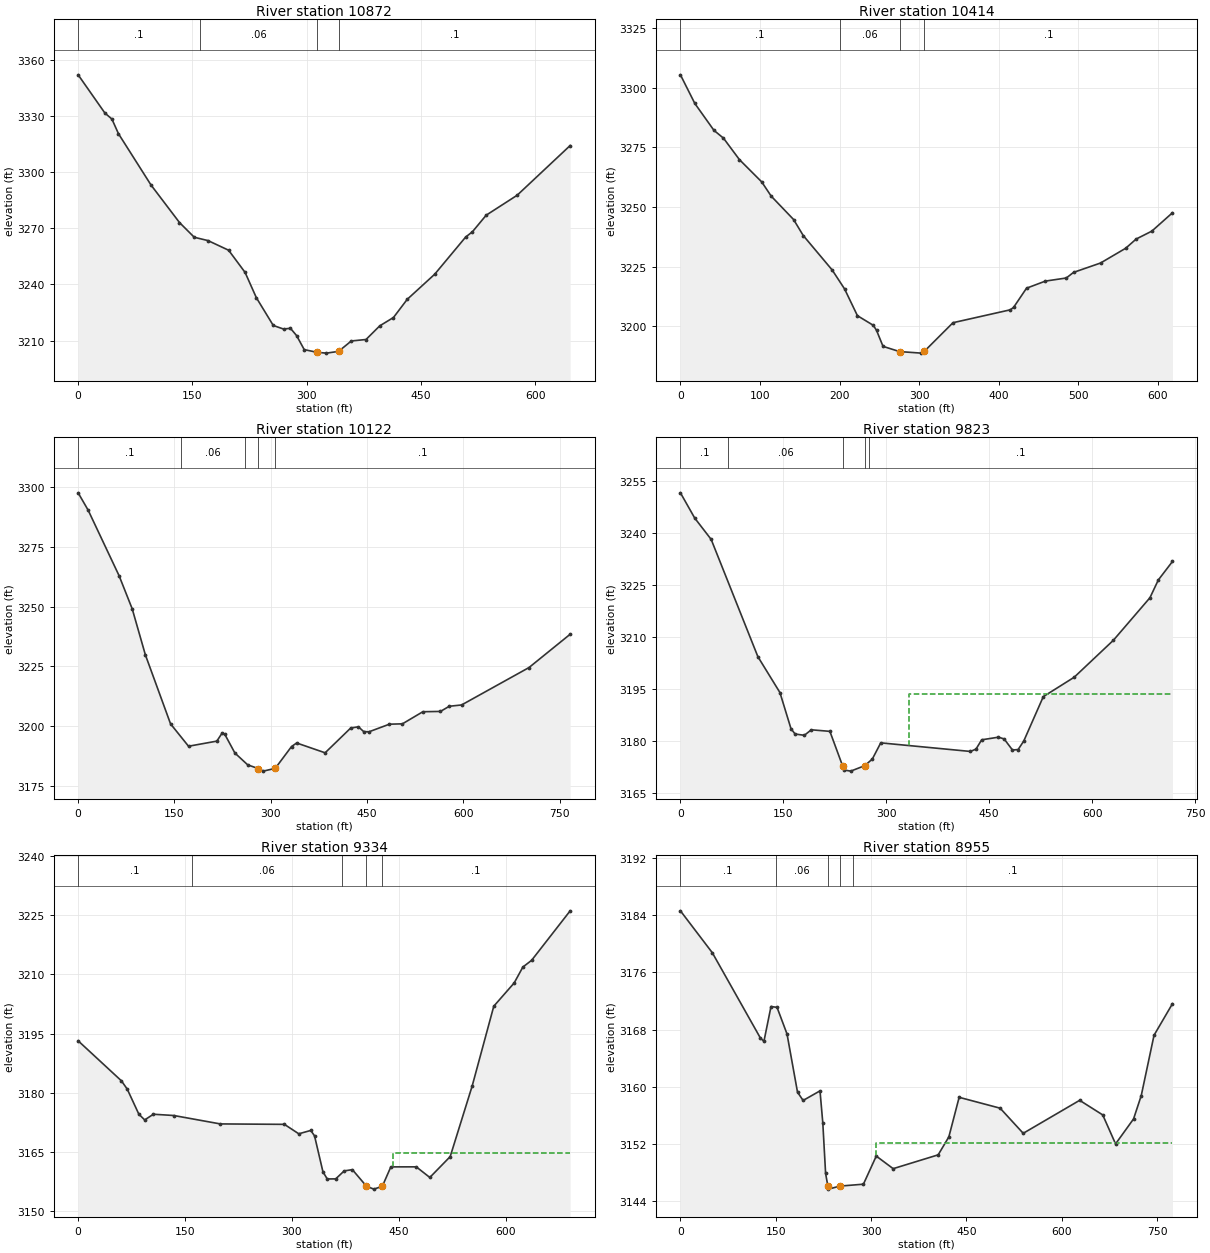
Type RM Length L Ch R = 1 ,10872   ,449.1,457.5,466
XS GIS Cut Line= 2
2195163.47578656495729.118828411 2194590.3531908496026.581501722
#Sta/Elev= 30
       0 3352.15    35.1 3331.71    44.3  3328.5    52.9 3320.66    95.6 3293.22
     133 3273.13   152.4 3265.25   170.5 3263.46   197.5 3258.31   219.1 3246.44
   233.9  3232.9   256.1 3218.06   269.5 3216.16   278.6 3216.56   286.7 3212.64
   296.7 3205.15     314 3203.67   325.9 3203.27   341.7  3204.2   358.5 3209.77
   377.8 3210.56   395.8 3217.86   413.8 3222.32   431.9 3232.06   467.9 3245.47
   508.5 3265.34   517.5 3268.23   535.5 3277.06   576.1 3287.72   645.7 3314.33
#Mann= 4 ,-1,0
       0      .1       0     160     .06       0     314    .045       0
   341.7      .1       0
Bank Sta=314,341.7
XS Rating Curve= 0 ,0
Exp/Cntr=0.3,0.1

Type RM Length L Ch R = 1 ,10414   ,293.2,292.5,292.1
XS GIS Cut Line= 3
2195026.20944681495435.1785549212194593.07486814495458.701315143
2194443.15582615495566.263691416
#Sta/Elev= 30
       0 3305.38    18.1 3293.38    42.1 3282.13    54.1 3278.85    74.1 3269.88
   102.2 3260.51     114 3254.59   142.2 3244.77   154.3 3238.08   190.7 3223.63
   206.3 3215.68   222.4  3204.5   242.4 3200.45   246.4 3198.37   254.6 3191.64
   275.33189.464   302.5 3188.81   306.5 3189.57   342.5 3201.55   414.6 3206.96
   418.7 3207.99   434.9    3216   458.6 3218.98   484.9 3220.28     494 3222.63
   527.9 3226.55   559.5 3232.73   572.7  3236.6   592.4 3239.91   618.3  3247.6
#Mann= 4 ,-1,0
       0      .1       0     200     .06       0   275.3    .045       0
   306.5      .1       0
Bank Sta=275.3,306.5
XS Rating Curve= 0 ,0
Exp/Cntr=0.3,0.1

Type RM Length L Ch R = 1 ,10122   ,300.3,298.1,294.9
XS GIS Cut Line= 3
2194987.71832343 495143.052924192194418.00678954495181.638964334
2194254.58356069495288.318016498
#Sta/Elev= 30
       0 3297.58    15.6 3290.32    63.7 3262.95    84.2 3249.06   104.7 3229.82
   143.9 3200.96   171.9  3191.6     216 3193.74   224.1 3197.07   228.1 3196.73
   244.1 3188.76   264.1  3183.8   280.43182.286   288.2 3181.19   306.9 3182.34
   332.3 3191.47   340.3 3192.96   384.6 3188.85   424.5 3199.23   436.5 3199.72
   444.6 3197.74   452.6 3197.61   484.7 3200.82     505 3200.97   536.8 3206.03
   564.2 3206.16     578 3208.32   597.1 3208.86   702.1 3224.51   766.2 3238.44
#Mann= 5 ,-1,0
       0      .1       0     160     .06       0     260      .1       0
   280.4    .045       0   306.9      .1       0
Bank Sta=280.4,306.9
XS Rating Curve= 0 ,0
Exp/Cntr(USF)=0,0
Exp/Cntr=0.3,0.1

Type RM Length L Ch R = 1 ,9823    ,482.8,489.1,498
XS GIS Cut Line= 3
 2194900.9188158494857.8774951112194745.85429116494848.975708839
2194196.06792237494963.783271999
#Sta/Elev= 30
       0 3251.66    20.8 3244.38    44.8 3238.21   112.9 3204.35     145 3194.01
   161.1 3183.58   167.1 3182.04   180.6 3181.67   190.7 3183.26   217.8 3182.81
  236.273172.871   238.8 3171.64   248.2 3171.33   268.5  3172.9   279.6  3174.8
   291.9 3179.49   422.6 3177.01   430.7 3177.69     439 3180.37   463.5 3181.13
   471.7 3180.62   483.9 3177.42   492.1 3177.56   500.3 3180.01   528.8 3192.83
   573.8 3198.43     631 3209.12   684.2 3221.38   696.4 3226.51     717 3231.84
#Mann= 5 ,-1,0
       0      .1       0      70     .06       0  236.27    .045       0
   268.5     .06       0  275.32      .1       0
#XS Ineff= 2 , 0
                          333.31         3193.47
Permanent Ineff=
       F       F
Bank Sta=236.27,268.5
XS Rating Curve= 0 ,0
Exp/Cntr=0.3,0.1

Type RM Length L Ch R = 1 ,9334    ,380.4,379.3,380.9
XS GIS Cut Line= 4
2194791.69460322494622.567933105  2194477.146353494558.724350624
2194355.01874505 494496.463217162194127.12637595 494542.91676727
#Sta/Elev= 30
       0 3193.19    60.7 3183.07    68.9 3180.97    85.2 3174.63    93.4 3173.17
   105.6 3174.61   134.2 3174.29   199.5 3172.16   289.5 3172.05   309.7 3169.66
   326.5 3170.51   331.8 3169.14   343.6 3160.04   349.6 3158.24   361.5 3158.25
   373.4 3160.27   384.9 3160.59   404.73156.391     415 3155.66   426.9 3156.36
   438.9 3161.29   474.6  3161.3   493.6 3158.61   522.2 3163.89   553.1 3181.78
   583.4 3201.95     612 3207.83   624.2 3211.85   636.5 3213.56   690.6 3226.08
#Mann= 5 ,-1,0
       0      .1       0     160     .06       0  370.96      .1       0
   404.7    .045       0   426.9      .1       0
#XS Ineff= 2 , 0
                          442.08         3164.85
Permanent Ineff=
       F       F
Bank Sta=404.7,426.9
XS Rating Curve= 0 ,0
Exp/Cntr=0.3,0.1

Type RM Length L Ch R = 1 ,8955    ,379.2,373.3,345
XS GIS Cut Line= 4
2194836.49735408494403.8295922242194710.62312369494273.139730573
2194542.99947494494193.5388562672194139.48418119494139.874249139
#Sta/Elev= 30
       0 3184.59    50.2 3178.73   125.9  3166.8   131.4 3166.36   142.5 3171.22
     152  3171.1   167.7 3167.38   184.2 3159.25     193 3158.09   219.6 3159.43
     224 3154.95   228.4 3147.89  231.923146.147   232.9  3145.7   250.6 3146.12
   287.9 3146.39   308.1 3150.32   334.7 3148.56   405.5 3150.49   422.3    3153
   438.5 3158.53     503 3157.01   539.3  3153.5   628.1 3158.11   664.4 3156.07
   684.6 3152.02   712.9 3155.51     725 3158.77   745.1  3167.2   774.1 3171.61
#Mann= 5 ,-1,0
       0      .1       0     150     .06       0  231.92    .045       0
   250.6     .06       0  271.45      .1       0
#XS Ineff= 2 , 0
                          307.83         3152.17
Permanent Ineff=
       F       F
Bank Sta=231.92,250.6
XS Rating Curve= 0 ,0
Exp/Cntr=0.3,0.1

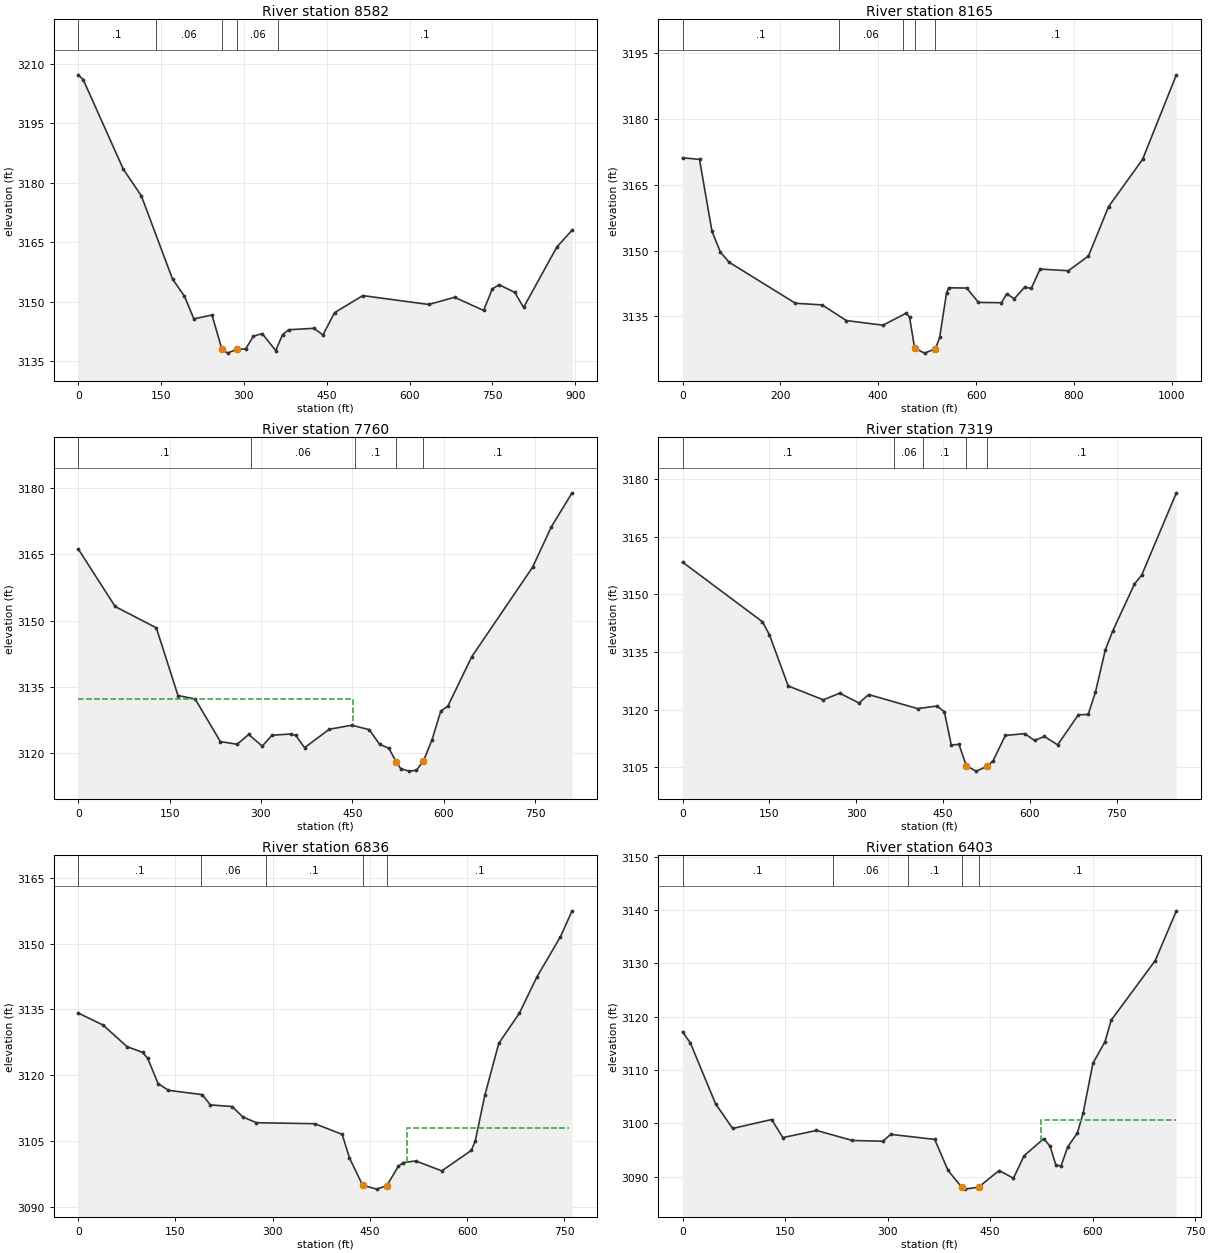
Type RM Length L Ch R = 1 ,8582    ,413.6,417.3,411.9
XS GIS Cut Line= 5
2194965.19937992493877.424686661 2194774.7998053493850.345489975
2194655.54844697493922.9423915972194579.76299823493988.760664427
2194120.87525118494041.754508972
#Sta/Elev= 30
       0 3207.25     9.1 3206.01    81.8 3183.38   114.2 3176.74   170.7 3155.71
   192.3 3151.39   209.4 3145.65   242.2 3146.64259.73213138.168   270.3 3137.01
287.4548 3138.02   303.1 3138.04   317.1 3141.28   333.1 3141.93   357.6 3137.66
   369.9 3141.67   381.3 3142.92   426.8 3143.27   443.1  3141.6   464.1 3147.22
   515.3 3151.53   634.5 3149.29   681.5  3151.1   733.9 3147.79     750 3153.25
   762.1 3154.28   790.3 3152.34   806.4 3148.55   866.8 3163.83   894.2 3168.04
#Mann= 5 ,-1,0
       0      .1       0     140     .06       0259.7321    .045       0
287.4548     .06       0  361.93      .1       0
Bank Sta=259.7321,287.4548
XS Rating Curve= 0 ,0
Exp/Cntr(USF)=0,0
Exp/Cntr=0.3,0.1

Type RM Length L Ch R = 1 ,8165    ,402.7,405,407.8
XS GIS Cut Line= 3
2194779.43986411493311.5619677482194152.40597463493848.168873709
2193972.60927523493887.500388477
#Sta/Elev= 30
       0 3171.17    34.7  3170.8    60.2  3154.4    77.2 3149.69    94.8 3147.36
   230.7 3137.97   285.5 3137.59   334.7 3134.02   409.7 3132.97   457.1  3135.7
   463.9 3134.83   474.4 3127.73   494.6 3126.59     517 3127.59   525.5 3130.16
   539.6 3140.34   543.9  3141.5   580.8 3141.44   604.9 3138.16   651.9 3138.09
   662.4 3140.11   678.2 3139.01   699.2 3141.64   712.7 3141.36   730.8 3145.77
   788.7 3145.39   829.7 3148.76   870.6 3159.99   940.2 3170.79  1009.3 3190.09
#Mann= 5 ,-1,0
       0      .1       0     320     .06       0     450      .1       0
   474.4    .045       0     517      .1       0
Bank Sta=474.4,517
XS Rating Curve= 0 ,0
Exp/Cntr=0.3,0.1

Type RM Length L Ch R = 1 ,7760    ,432.2,440.9,448.5
XS GIS Cut Line= 3
2194560.22340768493111.2289320532194401.75892576493152.777539396
 2193875.4209094493529.057812648
#Sta/Elev= 30
       0 3166.24    60.6 3153.22   128.2 3148.39   163.8 3133.07     192 3132.29
   233.3 3122.65   260.8 3122.04   279.9 3124.25   302.1 3121.62   318.2 3124.08
   348.7 3124.36   357.1 3124.03   371.7 3121.27   412.1 3125.43   449.1 3126.35
   477.8 3125.35   494.7 3122.05     510 3121.12   522.2 3118.02   529.4 3116.54
   542.8 3115.96   555.2 3116.15   566.7 3118.22     581 3123.11   595.3 3129.57
   606.8 3130.65     646 3141.83     746 3162.12   776.6  3171.2   810.8 3178.94
#Mann= 5 ,-1,0
       0      .1       0  283.82     .06       0  453.82      .1       0
   522.2    .045       0   566.7      .1       0
#XS Ineff= 2 , 0
          450.68 3132.24
Permanent Ineff=
       F       F
Bank Sta=522.2,566.7
XS Rating Curve= 0 ,0
Exp/Cntr=0.3,0.1

Type RM Length L Ch R = 1 ,7319    ,490.4,482.3,467.6
XS GIS Cut Line= 3
2194444.86163102492938.895074398 2194172.4681389492898.706074615
2193623.44135586493079.494805907
#Sta/Elev= 30
       0 3158.39   138.2 3142.84   150.3 3139.42   182.6 3126.14   243.3 3122.52
   271.6 3124.25   305.1 3121.69   321.6 3123.89   406.2 3120.24   439.9  3120.9
   452.5  3119.4   464.4 3110.78   477.8  3110.9   490.4 3105.32   507.3 3103.95
   526.2 3105.16   536.8 3106.69   557.8 3113.23   591.5 3113.72   608.3 3111.93
   625.2 3112.98   648.2  3110.8   684.1 3118.64     701  3118.7   713.6 3124.55
   730.5 3135.45   743.2 3140.38     781 3152.68   793.6 3155.04   853.4 3176.43
#Mann= 5 ,-1,0
       0      .1       0  365.34     .06       0  415.34      .1       0
   490.4    .045       0   526.2      .1       0
Bank Sta=490.4,526.2
XS Rating Curve= 0 ,0
Exp/Cntr=0.3,0.1

Type RM Length L Ch R = 1 ,6836    ,429.6,433.3,445.2
XS GIS Cut Line= 5
2194131.39618119492453.8877927162193942.46303968492454.413981199
2193762.95670336492508.4398582882193668.78282612492606.431595413
2193442.17333974492726.368003443
#Sta/Elev= 30
       0 3134.19    38.4 3131.45    75.2 3126.55    99.2 3125.24   107.2 3123.87
   123.2 3118.14   139.2  3116.6   191.3 3115.61   203.9 3113.27   237.3 3112.91
     254 3110.53   274.9 3109.22   365.1 3108.99   407.2 3106.56   418.5  3101.2
438.72773094.987   460.6  3094.1  476.183094.911   493.9 3099.32   501.6 3100.16
   520.7 3100.51   560.9 3098.26   606.5 3102.92   612.6 3105.11   627.2 3115.42
   648.8 3127.29   680.5 3134.14   707.6  3142.4   743.8 3151.52   761.9 3157.46
#Mann= 5 ,-1,0
       0      .1       0  188.93     .06       0  288.93      .1       0
438.7277    .045       0  476.18      .1       0
#XS Ineff= 1 ,-1
  506.82   757.6 3107.94
Permanent Ineff=
       F
Bank Sta=438.7277,476.18
XS Rating Curve= 0 ,0
Exp/Cntr=0.3,0.1

Type RM Length L Ch R = 1 ,6403    ,316.6,316.2,328.1
XS GIS Cut Line= 4
2193959.25882701492016.4864869022193744.27888416492065.588984325
2193479.24103953492224.5297034492193327.97706641  492344.3946829
#Sta/Elev= 30
       0 3117.12    11.4 3115.08    48.3 3103.67    73.3 3099.02   130.4  3100.7
   146.8 3097.31     196 3098.65   248.6 3096.77   293.2 3096.63   304.6 3097.92
     369 3096.97   388.5 3091.16   408.4 3088.03   412.7 3087.65   433.1 3088.01
   463.2 3091.14   484.2 3089.69   499.7 3093.89   528.5 3097.12   537.9 3095.68
   546.4 3092.11   553.9 3091.99   563.5 3095.55   577.8 3098.19   586.3 3101.97
   600.5 3111.24   618.2  3115.3   627.2 3119.31   691.7  3130.5   722.6 3139.82
#Mann= 5 ,-1,0
       0      .1       0     220     .06       0  330.52      .1       0
   408.4    .045       0   433.1      .1       0
#XS Ineff= 2 , 0
                          525.07         3100.57
Permanent Ineff=
       F       F
Bank Sta=408.4,433.1
XS Rating Curve= 0 ,0
Exp/Cntr=0.3,0.1

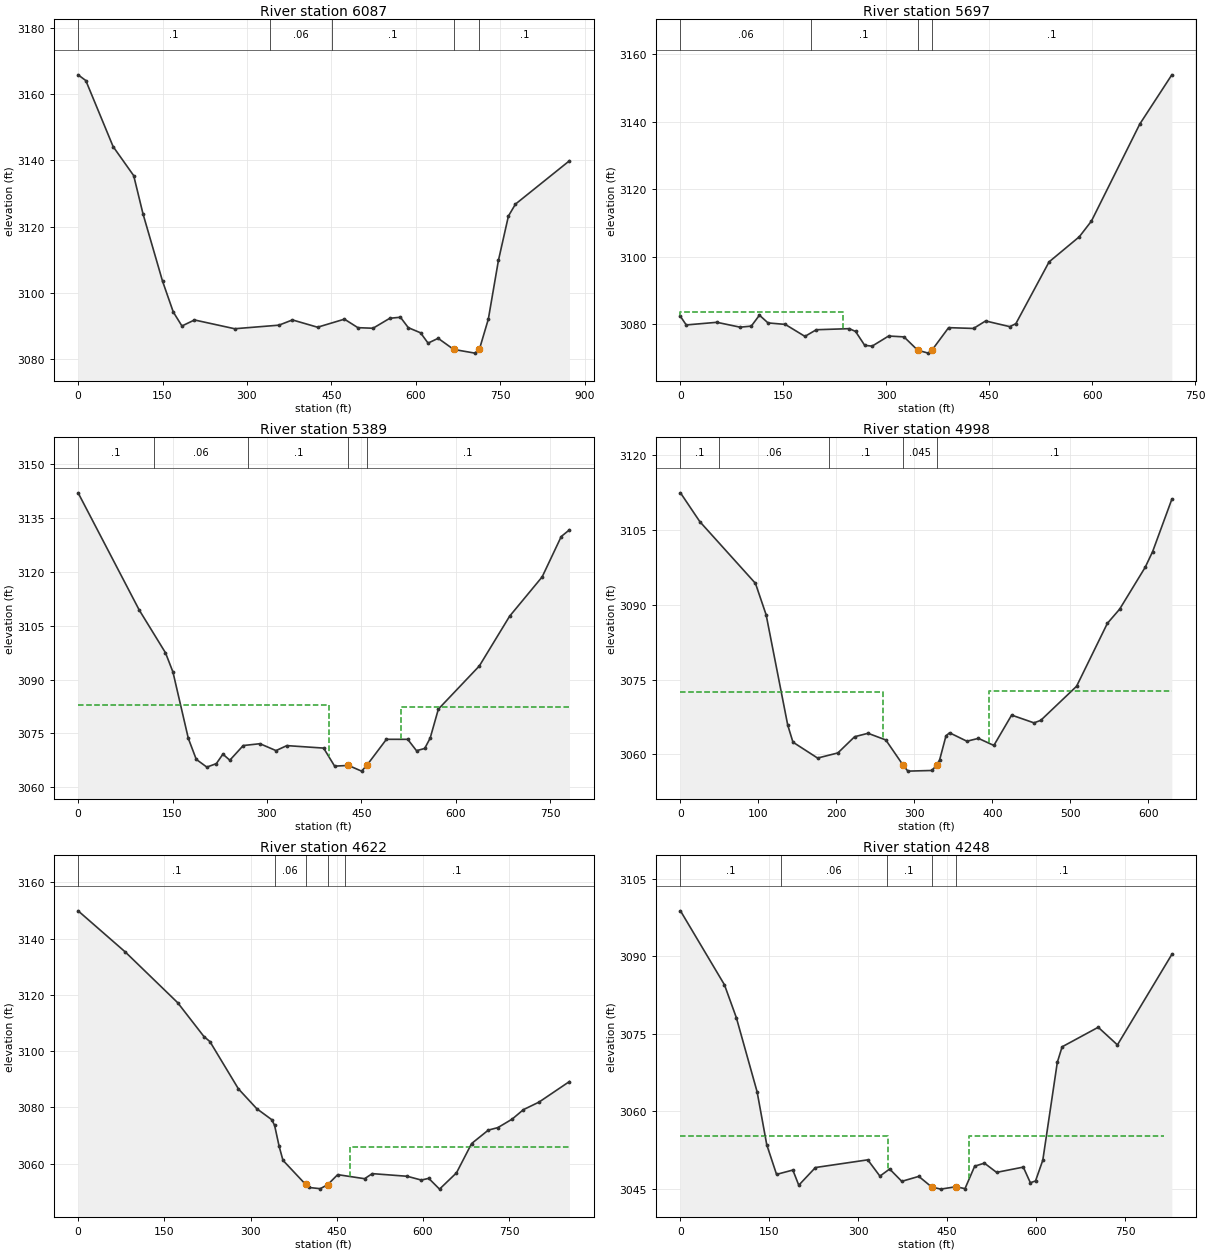
Type RM Length L Ch R = 1 ,6087    ,441,390.1,448.7
XS GIS Cut Line= 3
2193944.00577904491642.0235660482193787.10166594 491732.74445843
2193166.99761577 492039.75102501
#Sta/Elev= 30
       0 3165.82    13.7 3164.09    62.2 3144.17    98.8 3135.39   115.3 3123.88
   150.1 3103.51   169.1 3094.25   184.5 3090.02   206.8 3091.84   278.2 3089.19
   356.9 3090.27   380.9 3091.85   425.5 3089.65   473.3 3092.08   497.2 3089.51
   524.1 3089.34   553.9 3092.35   572.8 3092.66   586.8 3089.51   608.5 3087.97
   621.9 3084.85   639.8  3086.3   667.4 3082.95   705.1 3081.83  713.283083.079
     729  3092.1   746.9 3109.79   764.7  3123.2   777.2  3126.8   873.2 3139.89
#Mann= 5 ,-1,0
       0      .1       0  341.24     .06       0  451.24      .1       0
   667.4    .045       0  713.28      .1       0
Bank Sta=667.4,713.28
XS Rating Curve= 0 ,0
Exp/Cntr=0.3,0.1

Type RM Length L Ch R = 1 ,5697    ,345.7,307.4,350.7
XS GIS Cut Line= 3
2193531.46015691 491482.229738752193341.80026786491532.631898395
2192869.71968546 491750.38399466
#Sta/Elev= 30
       0 3082.36     8.4 3079.83    53.1 3080.61    86.8 3079.17   103.2 3079.48
   115.1 3082.72   127.6 3080.43   152.7 3079.99   181.4 3076.44     198 3078.41
   246.1 3078.73   255.2 3077.89   268.5 3073.79   279.3 3073.55   303.4 3076.55
   325.8 3076.29   345.6 3072.37   345.6 3072.36     361 3071.48   366.7 3072.41
   390.8 3079.03   427.1 3078.79   444.7 3081.01     480 3079.32   488.8 3080.21
   537.2 3098.51   581.3 3105.96   598.9 3110.59   669.4 3139.34   716.1 3153.92
#Mann= 4 ,-1,0
       0     .06       0     190      .1       0   345.6    .045       0
   366.7      .1       0
#XS Ineff= 2 , 0
          237.07 3083.58
Permanent Ineff=
       F       F
Bank Sta=345.6,366.7
XS Rating Curve= 0 ,0
Exp/Cntr(USF)=0,0
Exp/Cntr=0.3,0.1

Type RM Length L Ch R = 1 ,5389    ,390.6,391.4,389.2
XS GIS Cut Line= 3
2193381.01025132491081.4307669972193123.80193933491307.922470391
2192720.13626019491477.579450625
#Sta/Elev= 30
       0 3142.06      97 3109.43   138.8 3097.49   150.6 3092.16   175.1 3073.62
   187.7 3067.79   204.5 3065.63   219.6  3066.6     230 3069.24     241 3067.55
   262.3 3071.64   288.9 3072.15   314.4 3070.23   331.6 3071.62     390 3070.93
   407.5  3065.9 429.4553066.097   450.3 3064.51 458.5553066.102   489.8 3073.38
   523.6 3073.37   537.6  3070.2   550.6 3070.83   559.3 3073.72   572.3 3081.79
   637.4 3093.82   685.5 3107.68   737.2 3118.64   767.5 3129.88   780.6 3131.76
#Mann= 5 ,-1,0
       0      .1       0     120     .06       0     270      .1       0
 429.455    .045       0 458.555      .1       0
#XS Ineff= 2 , 0
           398.6  3082.9  512.28         3082.26
Permanent Ineff=
       F       F
Bank Sta=429.455,458.555
XS Rating Curve= 0 ,0
Exp/Cntr=0.3,0.1

Type RM Length L Ch R = 1 ,4998    ,385.7,375.6,365.1
XS GIS Cut Line= 4
2193033.41021015490822.6155023872192875.76421598490998.991144797
2192770.92917632491055.5146977882192612.48466151491279.828099329
#Sta/Elev= 30
       0 3112.48    24.9 3106.69    96.2 3094.32   109.9 3088.01   137.6 3065.89
   144.3 3062.47   175.9 3059.28   201.9 3060.31   223.4 3063.56   240.6 3064.25
   263.4 3062.91285.80913057.806   291.7 3056.66   322.4 3056.79   328.8 3057.88
   332.4 3058.89   340.6 3063.74   345.2 3064.35   367.4 3062.66   382.2 3063.23
     402 3061.81   424.8  3067.9   453.5 3066.34   462.2 3066.85   508.1 3073.68
   547.6  3086.3   563.4 3089.16   596.2 3097.57   605.7 3100.71   630.3  3111.2
#Mann= 5 ,-1,0
       0      .1       0      50     .06       0     190      .1       0
285.8091    .045       0   328.8      .1       0
#XS Ineff= 2 , 0
          259.25 3072.58  395.46         3072.72
Permanent Ineff=
       F       F
Bank Sta=285.8091,328.8
XS Rating Curve= 0 ,0
Exp/Cntr=0.3,0.1

Type RM Length L Ch R = 1 ,4622    ,382.9,374.5,362.5
XS GIS Cut Line= 5
2192925.49793957490456.1695887142192674.96779556490642.878753861
 2192588.7600723490754.9487940962192547.64201523490789.593194267
2192367.54710629491086.545532826
#Sta/Elev= 30
       0 3149.91      82 3135.29   173.2 3117.25   218.9 3105.21   229.3 3103.42
   278.9  3086.6   310.9 3079.53   336.7 3075.67   341.8 3073.66   349.8 3066.12
   356.4 3061.19   395.9  3052.6   401.7 3051.52   421.3  3051.1434.19173052.526
   451.6 3056.09   498.4 3054.65   511.8 3056.45   572.6 3055.51   597.2 3054.16
     610 3054.78   628.8 3050.94   658.3 3056.73   684.6 3067.15   713.7 3071.93
   730.3 3072.82   755.1 3075.83   774.8 3079.21   801.8 3081.88   854.9 3089.21
#Mann= 5 ,-1,0
       0      .1       0  342.45     .06       0   395.9    .045       0
434.1917     .06       0  463.84      .1       0
#XS Ineff= 2 , 0
                          473.59         3065.78
Permanent Ineff=
       F       F
Bank Sta=395.9,434.1917
XS Rating Curve= 0 ,0
Exp/Cntr(USF)=0,0
Exp/Cntr=0.3,0.1

Type RM Length L Ch R = 1 ,4248    ,451.2,477.2,494.4
XS GIS Cut Line= 4
2192468.07732312490278.0636601992192288.11063744490515.722362055
2192214.15349647490843.3279710082192182.29011089491035.747530169
#Sta/Elev= 30
       0 3098.85    74.2 3084.51    94.2 3078.16   129.3 3063.76   145.6 3053.48
   162.1 3047.74   189.6 3048.58   199.6 3045.64   227.7 3049.07     316 3050.56
   336.5  3047.4   352.9 3048.78   373.4 3046.39   402.1 3047.35423.71133045.305
     439 3044.88464.91083045.345     480 3044.97   496.4 3049.33   512.8 3049.92
   533.3 3048.13   578.4 3049.15   590.3 3046.12     599 3046.46   611.3 3050.49
   635.8 3069.48   643.9 3072.48   704.8 3076.27   737.2 3072.85     829  3090.4
#Mann= 5 ,-1,0
       0      .1       0     170     .06       0  348.11      .1       0
423.7113    .045       0464.9108      .1       0
#XS Ineff= 2 ,-1
       0     350 3055.19  486.97   816.1 3055.19
Permanent Ineff=
       F       F
Bank Sta=423.7113,464.9108
XS Rating Curve= 0 ,0
Exp/Cntr=0.3,0.1

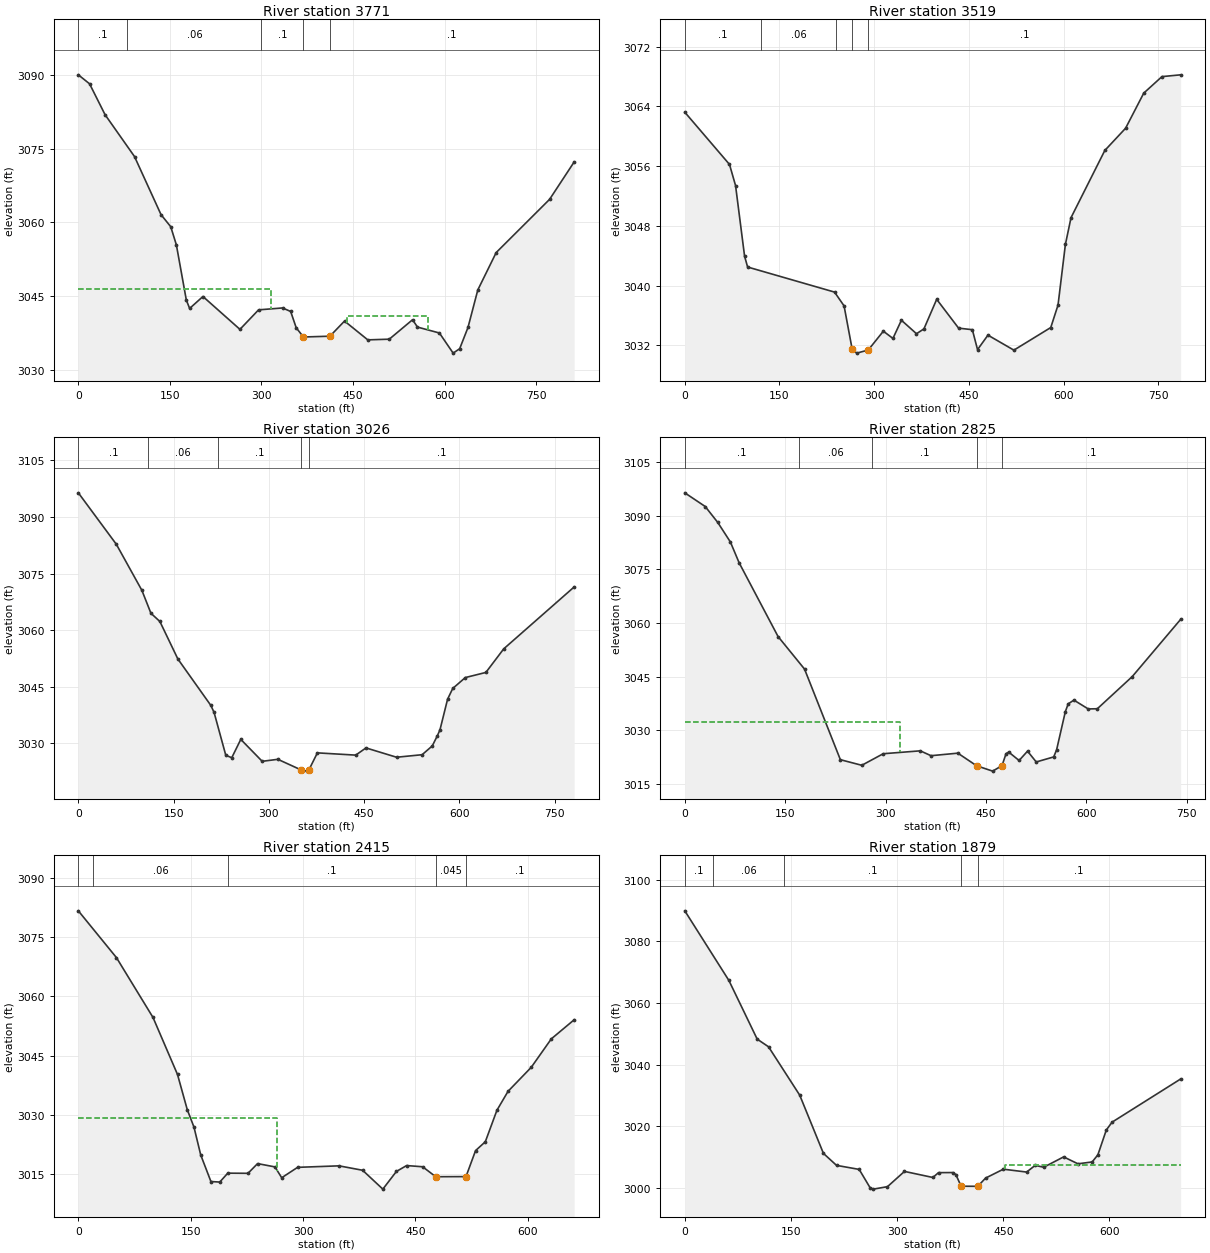
Type RM Length L Ch R = 1 ,3771    ,262.7,251.8,237.5
XS GIS Cut Line= 4
2192175.81526793490114.8791212562191968.92764689 490340.18312316
2191837.45495876490416.2200115162191662.10484802490724.087607485
#Sta/Elev= 30
       0 3090.02    18.4 3088.19    43.8  3081.9      92 3073.38   135.5 3061.54
   151.4 3059.08   160.6 3055.38   176.9 3044.15   182.3 3042.45   204.1 3044.88
   264.7 3038.19   295.2 3042.16   334.5 3042.55   347.8 3041.83   356.9  3038.5
368.72343036.635412.10473036.797     436 3039.88   474.1 3036.05   509.3 3036.19
   547.4 3040.15   555.5 3038.65   591.4 3037.45   613.9 3033.35   624.6 3034.25
   638.2 3038.57   654.3 3046.22   684.4 3053.83   771.9 3064.67   812.1 3072.28
#Mann= 5 ,-1,0
       0      .1       0      80     .06       0     300      .1       0
368.7234    .045       0412.1047      .1       0
#XS Ineff= 2 ,-1
       0  316.06 3046.43  439.46  572.41 3040.97
Permanent Ineff=
       F       F
Bank Sta=368.7234,412.1047
XS Rating Curve= 0 ,0
Exp/Cntr(USF)=0,0
Exp/Cntr=0.3,0.1

Type RM Length L Ch R = 1 ,3519    ,511.5,492.8,464.7
XS GIS Cut Line= 3
2191869.21142406 489977.907739572191644.01839117490322.662021882
2191556.95922897490685.988925463
#Sta/Elev= 30
       0 3063.23    70.8 3056.23    80.4  3053.4    94.7 3043.93    99.5 3042.48
   237.2 3039.12   252.3 3037.27   265.2 3031.43   272.5 3030.94   290.6 3031.36
   314.5 3033.88   329.7 3032.91   343.1 3035.35     367 3033.54   378.8 3034.19
     399 3038.15   433.7 3034.29   455.5 3034.08   463.7 3031.41   480.2 3033.35
   521.3 3031.34   579.7 3034.37   591.2 3037.38   602.9 3045.52   611.8  3049.1
   665.3  3058.1   698.2 3061.08     727 3065.79   755.8    3068   785.4 3068.24
#Mann= 5 ,-1,0
       0      .1       0     120     .06       0     240      .1       0
   265.2    .045       0   290.6      .1       0
Bank Sta=265.2,290.6
XS Rating Curve= 0 ,0
Exp/Cntr(USF)=0,0
Exp/Cntr=0.3,0.1

Type RM Length L Ch R = 1 ,3026    ,200,200.8,213
XS GIS Cut Line= 4
2191385.83308177489888.3033867772191247.44649552490109.634055923
2191279.83250385490237.0886693842191244.24639129490623.628875603
#Sta/Elev= 30
       0 3096.38    59.9 3082.73   100.1 3070.53   114.3 3064.47   128.4 3062.29
   156.7 3052.36   208.6 3040.06   213.7 3038.22   232.2 3026.83   241.6  3026.2
   255.8 3031.05   289.5 3025.24   314.2 3025.77   350.1 3023.01   359.6 3022.64
   363.3 3023.05   376.4 3027.48   436.8 3026.88   452.9 3028.79   501.1 3026.32
   541.3 3026.99   557.3 3029.32   565.4 3032.05   569.4 3033.57   581.4  3041.7
   589.5 3044.54   609.3 3047.43   641.7 3048.79   669.8 3055.04   780.7 3071.44
#Mann= 5 ,-1,0
       0      .1       0     110     .06       0     220      .1       0
   350.1    .045       0   363.3      .1       0
Bank Sta=350.1,363.3
XS Rating Curve= 0 ,0
Exp/Cntr=0.3,0.1

Type RM Length L Ch R = 1 ,2825    ,399,410.2,407.4
XS GIS Cut Line= 4
2191249.83371091489835.1732162992191087.92999445 490098.75107373
2191079.07451024490301.7973178542190989.29758308490511.520812603
#Sta/Elev= 30
       0 3096.39    30.5 3092.57    49.2 3088.13    68.1 3082.66    81.2 3076.83
   139.3 3056.25   178.9 3047.14   232.4 3021.84   264.4 3020.27   296.4  3023.5
   351.8 3024.31   367.8 3022.95   407.9 3023.66   435.9 3020.14   459.9 3018.64
473.84673020.164   479.9 3023.51   483.9 3023.96   499.4 3021.61     512 3024.22
     525  3021.2   551.1 3022.61   555.4 3024.57   568.5 3035.28   572.8 3037.44
   581.3 3038.48   602.7 3036.01   616.3 3036.07   668.5 3045.07   740.7 3061.03
#Mann= 5 ,-1,0
       0      .1       0     170     .06       0     280      .1       0
   435.9    .045       0473.8467      .1       0
#XS Ineff= 2 , 0
          320.74  3032.5
Permanent Ineff=
       F       F
Bank Sta=435.9,473.8467
XS Rating Curve= 0 ,0
Exp/Cntr(USF)=0,0
Exp/Cntr=0.3,0.1

Type RM Length L Ch R = 1 ,2415    ,534.2,535.5,536
XS GIS Cut Line= 4
 2190901.3071534489803.9467587352190696.42449563490200.742798182
2190664.96306604490303.1466670392190618.92562696 490401.01269589
#Sta/Elev= 30
       0  3081.6    50.9 3069.76    99.7 3054.62   132.4  3040.2   145.4 3031.32
   154.4 3026.87   163.4 3019.84     177 3013.12   188.8 3012.99   199.5 3015.24
   226.5  3015.2   239.3 3017.66   262.5 3016.82   271.5 3014.08   292.7 3016.71
     348 3017.09   379.5 3015.97   406.5  3011.2   424.6 3015.67   438.2 3017.16
   459.6 3016.86   477.1 3014.34   517.5 3014.37   530.3 3020.95   543.3 3023.18
   558.8 3031.15   573.6 3035.93   604.6 3042.01   631.4 3049.21   661.9 3054.04
#Mann= 5 ,-1,0
       0      .1       0      20     .06       0     200      .1       0
   477.1    .045       0   517.5      .1       0
#XS Ineff= 2 , 0
          265.59 3029.26
Permanent Ineff=
       F       F
Bank Sta=477.1,517.5
XS Rating Curve= 0 ,0
Exp/Cntr(USF)=0,0
Exp/Cntr=0.3,0.1

Type RM Length L Ch R = 1 ,1879    ,473.2,491.8,501.3
XS GIS Cut Line= 5
2190260.55626228489546.8850901042190268.50300584489847.706993959
2190265.07873678489917.6123902662190236.61020199490008.107241854
2190264.50778492490241.233476028
#Sta/Elev= 30
       0 3089.89    62.3 3067.29   102.3 3048.25   118.3 3045.77   162.4 3030.06
   195.9 3011.16   214.4 3007.28   246.4 3005.97   261.7 3000.07   266.4 2999.57
   286.4 3000.37   310.4 3005.32   350.5 3003.35   358.5 3004.92   378.8 3004.95
     383 3004.31   390.4 3000.52   413.9 3000.48     425 3003.15   450.1 3006.04
     483 3005.11   495.1 3007.28   507.1 3006.67   535.3 3010.03   555.5 3007.79
   575.6 3008.39   583.7 3010.71   595.6 3018.77   603.8 3021.31   700.6 3035.31
#Mann= 5 ,-1,0
       0      .1       0      40     .06       0     140      .1       0
   390.4    .045       0   413.9      .1       0
#XS Ineff= 2 , 0
                           452.4         3007.51
Permanent Ineff=
       F       F
Bank Sta=390.4,413.9
XS Rating Curve= 0 ,0
Exp/Cntr(USF)=0,0
Exp/Cntr=0.3,0.1

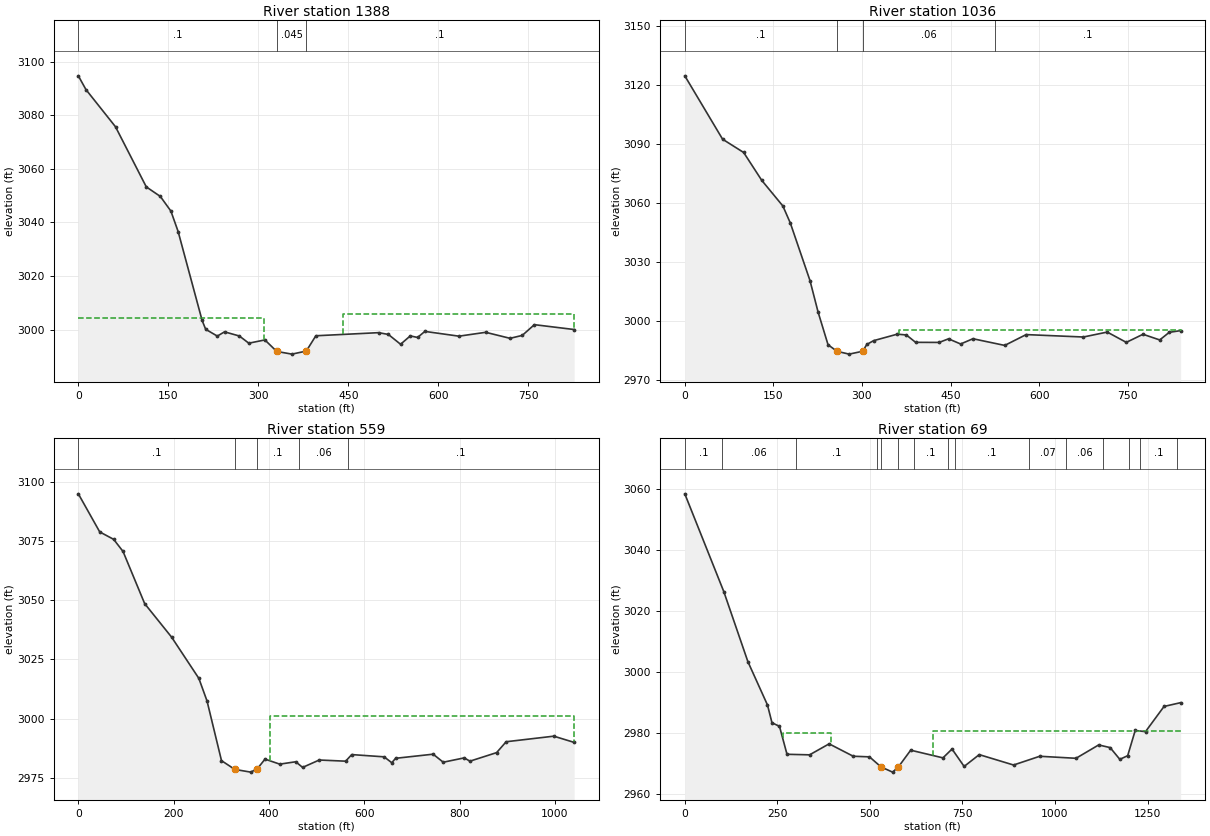
Type RM Length L Ch R = 1 ,1388    ,354.7,351.1,345.8
XS GIS Cut Line= 4
2190093.57095881489484.7372491462189968.18061442489641.418303679
2189752.91273864489834.5282026692189697.07388416490166.626988205
#Sta/Elev= 30
       0 3094.66    12.7 3089.53      62 3075.64   113.3 3053.22   136.7 3049.66
   154.3  3044.2   166.4 3036.55   206.3 3003.43   212.3 3000.09   231.7 2997.55
   243.7 2999.14   268.5 2997.58   284.2  2994.9     311 2996.12 330.796 2991.82
   356.1 2990.82     380 2991.96     396 2997.67   500.7 2998.83   516.9 2998.16
   537.2  2994.5   553.4 2997.62   565.6 2997.04   577.7  2999.3   634.5 2997.52
   679.1 2998.96   719.7 2996.72     740  2997.8   760.3 3001.81   826.6    3000
#Mann= 3 ,-1,0
       0      .1       0 330.796    .045       0     380      .1       0
#XS Ineff= 2 , 0
          308.78 3004.21  441.83         3005.89
Permanent Ineff=
       F       F
Bank Sta=330.796,380
XS Rating Curve= 0 ,0
Exp/Cntr=0.3,0.1

Type RM Length L Ch R = 1 ,1036    ,478.1,477.3,475.8
XS GIS Cut Line= 3
2189791.08824657489266.9879183612189471.06920141489671.224579446
2189426.54640418489992.318423016
#Sta/Elev= 30
       0 3124.56      64 3092.35    99.7 3085.59   130.3 3071.44   166.1 3058.39
   178.7 3049.75     212  3020.5   225.7 3004.52   242.6 2987.86   257.9 2984.52
   278.3  2983.1   301.1 2984.55   308.3 2988.03   319.7 2989.94   359.9 2993.25
   375.2 2992.84   390.9 2989.09   430.8 2989.05   446.6 2990.88   467.1 2988.26
     488 2990.92   541.8 2987.53   578.1 2993.03     675  2991.8   715.4 2994.31
   747.7 2989.08     776 2993.19   804.3 2990.31   820.4 2994.17   839.7 2995.05
#Mann= 4 ,-1,0
       0      .1       0   257.9    .045       0   301.1     .06       0
  525.58      .1       0
#XS Ineff= 2 , 0
                          362.74         2995.26
Permanent Ineff=
       F       F
Bank Sta=257.9,301.1
XS Rating Curve= 0 ,0
Exp/Cntr=0.3,0.1

Type RM Length L Ch R = 1 ,559     ,491.3,490,493.3
XS GIS Cut Line= 4
2189548.19896038489078.0427723972189290.07197042489129.337238351
2189146.83659666489325.9439340712189152.52883575489859.863220913
#Sta/Elev= 30
       0 3094.87    44.9  3078.8    74.1 3075.67    93.8 3070.56   139.2 3048.55
   195.8 3034.38   252.9 3017.01   270.1 3007.44   300.4  2982.3328.38232978.601
   361.8 2977.46375.66942978.901   391.7 2982.95   422.6 2980.83   456.2 2981.83
   470.6 2979.45   505.5 2982.57   560.9 2982.08   573.7 2984.86   641.7 2983.91
   657.7 2981.42   665.7 2983.29   744.5 2985.03   765.7 2981.64   809.7 2983.47
   821.7 2982.08   877.7 2985.69   897.7 2990.28   997.7 2992.63  1040.4    2990
#Mann= 5 ,-1,0
       0      .1       0328.3823    .045       0375.6694      .1       0
  463.17     .06       0  566.42      .1       0
#XS Ineff= 2 , 0
                          401.16         3001.18
Permanent Ineff=
       F       F
Bank Sta=328.3823,375.6694
XS Rating Curve= 0 ,0
Exp/Cntr(USF)=0,0
Exp/Cntr=0.3,0.1

Type RM Length L Ch R = 1 ,69      ,,,
XS GIS Cut Line= 4
2189415.86700082488694.803951921 2188953.0614958488778.558356703
2188836.86866834488928.6214077762188700.11599504489593.980885557
#Sta/Elev= 30
       0 3058.33   105.4 3026.31   170.4  3003.4   223.3 2989.22   235.5  2983.4
   255.8 2982.21   276.1 2973.07   337.1 2972.89   389.9 2976.49     455 2972.43
   498.9 2972.23529.96532968.949   561.2 2967.23 576.7282968.891   610.2 2974.41
   697.4  2971.9   721.9 2974.79   754.6 2969.09   795.4 2972.96   888.1 2969.56
   958.8 2972.42  1056.8 2971.76    1118 2976.13    1149 2975.26  1175.2 2971.41
  1196.4 2972.62  1216.7 2980.86  1244.6 2980.49  1294.6 2988.73  1339.4 2989.97
#Mann= 15 ,-1,0
       0      .1       0     100     .06       0     300      .1       0
  520.32     .07       0529.9653    .045       0 576.728     .07       0
  620.32      .1       0  710.11     .06       0  730.11      .1       0
  930.11     .07       0 1030.11     .06       0 1130.11      .1       0
 1200.11     .06       0 1230.11      .1       0 1330.11     .06       0
#XS Ineff= 2 ,-1
     264     394    2980  671.11  1396.8 2980.76
Permanent Ineff=
       F       F
Bank Sta=529.9653,576.728
XS Rating Curve= 0 ,0
Exp/Cntr(USF)=0,0
Exp/Cntr=0.3,0.1
LCMann Table=0

Chan Stop Cuts=-1
Use User Specified Reach Order=0
Composite Channel Slope=5